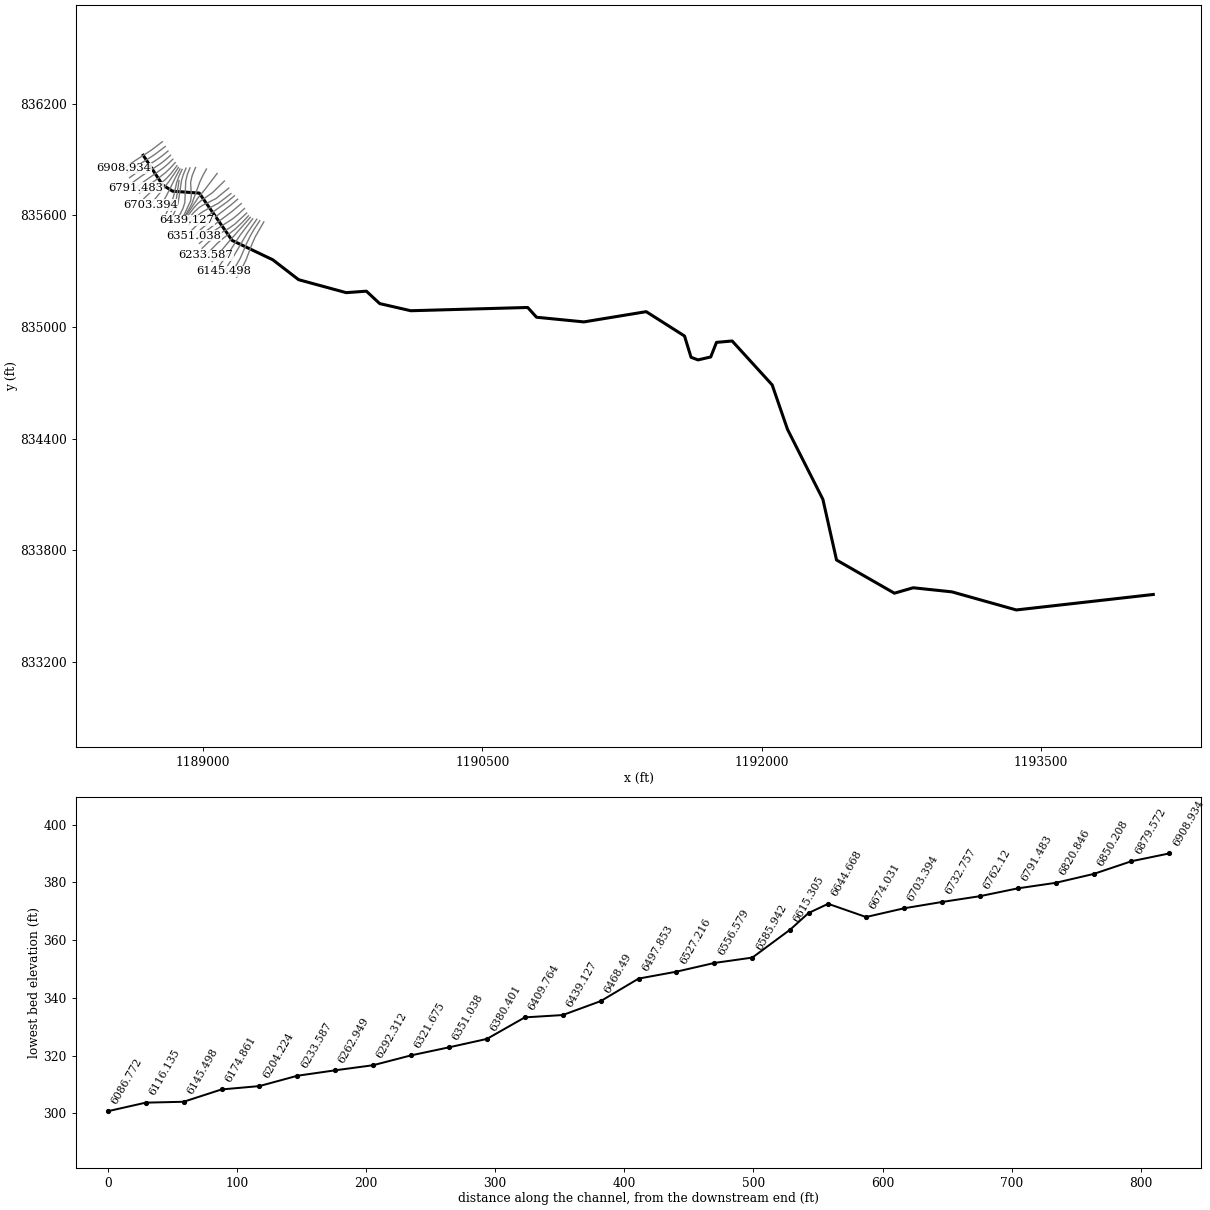
--- 79_ras.prj (project) ---

Proj Title=79
Current Plan=p01
Default Exp/Contr=0.3,0.1
English Units
Geom File=g01
Flow File=f01
Plan File=p01
Y Axis Title=Elevation
X Axis Title(PF)=Main Channel Distance
X Axis Title(XS)=Station
BEGIN DESCRIPTION:
RFD model 79 exported to HEC-RAS
END DESCRIPTION:

--- 79_ras.p01 (plan) ---

Plan Title=Plan 01
Program Version=4.10
Short Identifier=Plan 01
Geom File=g01
Flow File=f01
Subcritical Flow
Calc Critical at every XS
Secant Critical Depth

--- 79_ras.f01 (steady flow) ---

Flow Title=Flow 01
Program Version=4.10
Number of Profiles= 5
Profile Names=10yr,25yr,50yr,100yr,500yr
River Rch & RM=79,95,6908.934
   93.03  164.43  232.51  313.16  545.79
River Rch & RM=79,95,6615.305
  100.55  178.03  252.14  340.21  595.74
River Rch & RM=79,95,6497.853
  107.43  190.48  270.16  365.07  641.85
River Rch & RM=79,95,6380.401
  116.17  206.33  293.12  396.79  700.94
River Rch & RM=79,95,6233.587
  119.28  211.98  301.32  408.14  722.15
River Rch & RM=79,95,6145.498
  126.75  225.56  321.02  435.42  773.27
River Rch & RM=79,95,6057.409
  134.83  240.25  342.38  465.04  828.98
River Rch & RM=79,95,5939.957
  141.65  252.68  360.47  490.16  876.37
River Rch & RM=79,95,5851.868
  144.75  258.33  368.69  501.59  897.99
River Rch & RM=79,95,5763.779
  147.22  262.85  375.28  510.74  915.32
River Rch & RM=79,95,5655.238
  154.65   276.4  395.03  538.22  967.46
River Rch & RM=79,95,5555.606
  155.26  277.53  396.68  540.52  971.82
River Rch & RM=79,95,5455.974
  188.54  338.45  485.73  664.78 1209.41
River Rch & RM=79,95,5306.527
  194.07  348.59  500.59  685.57 1249.42
River Rch & RM=79,95,5227.214
  203.27   365.5  525.38  720.26 1316.36
River Rch & RM=79,95,5107.264
  206.95  372.26  535.29  734.16 1343.22
River Rch & RM=79,95,5007.632
  211.24  380.14  546.87  750.38 1374.61
River Rch & RM=79,95,4908.001
  216.75  390.28  561.75  771.26 1415.06
River Rch & RM=79,95,4808.369
  222.25  400.41  576.64  792.15 1455.61
River Rch & RM=79,95,4708.738
  229.59  413.92  596.51  820.04 1509.83
River Rch & RM=79,95,4609.106
  241.19   435.3  627.97  864.26 1596.02
River Rch & RM=79,95,4509.475
  249.12  449.93  649.51  894.56 1655.22
River Rch & RM=79,95,4409.843
  253.99  458.93  662.77  913.22 1691.75
River Rch & RM=79,95,4310.212
  255.21  461.18  666.09  917.89 1700.89
River Rch & RM=79,95,4115.378
  263.12   475.8  687.64  948.25 1760.41
River Rch & RM=79,95,3952.937
  267.99  484.79  700.91  966.95 1797.13
River Rch & RM=79,95, 3756.33
  273.46  494.91  715.85     988 1838.51
River Rch & RM=79,95,3590.234
  479.45  878.47  1285.7 1797.22 3460.36
River Rch & RM=79,95,3363.115
  486.03  890.78 1304.09  1823.5 3513.85
River Rch & RM=79,95,3166.507
  503.95  924.35 1354.27 1895.21 3660.09
River Rch & RM=79,95,2967.655
  548.66 1008.24 1479.82  2074.9 4027.86
River Rch & RM=79,95,2773.292
  556.99  1023.9 1503.27  2108.5 4096.84
River Rch & RM=79,95,2576.684
  561.16 1031.72    1515 2125.31 4131.36
River Rch & RM=79,95,2380.077
  564.13 1037.31 1523.38 2137.32 4156.04
River Rch & RM=79,95,2183.469
  570.08 1048.49 1540.13 2161.34 4205.43
River Rch & RM=79,95,1986.861
  572.46 1052.96 1546.84 2170.96  4225.2
River Rch & RM=79,95,1790.254
  679.82 1255.16 1850.53 2607.31 5127.72
River Rch & RM=79,95,1593.646
  699.93 1293.11 1907.65 2689.57 5298.87
River Rch & RM=79,95,1397.039
 1079.21 2012.85 2996.57 4266.46  8629.6
River Rch & RM=79,95,1298.735
 1088.54 2030.64 3023.62 4305.81 8713.74
River Rch & RM=79,95,1133.173
  1104.3 2060.68 3069.26 4372.23 8855.89
River Rch & RM=79,95,736.6966
 1127.04 2104.05  3135.2 4468.23 9061.55
River Rch & RM=79,95,587.2858
 1137.53 2124.07 3165.65 4512.57 9156.61
River Rch & RM=79,95,408.3278
 1141.02 2130.74  3175.8 4527.35 9188.32
River Rch & RM=79,95,266.9509
 1146.85 2141.86 3192.71 4551.98 9241.18
Boundary for River Rch & Prof#=79,95,1
Up Type= 0
Dn Type= 2
Boundary for River Rch & Prof#=79,95,2
Up Type= 0
Dn Type= 2
Boundary for River Rch & Prof#=79,95,2
Up Type= 0
Dn Type= 2
Boundary for River Rch & Prof#=79,95,2
Up Type= 0
Dn Type= 2
Boundary for River Rch & Prof#=79,95,2
Up Type= 0
Dn Type= 2

--- 79_ras.g01 (geometry) ---

Geom Title=79
Program Version=4.10

River Reach=79,95
Reach XY= 30
1188677.43935087835922.8381211461188781.64522746835763.145998582
1188835.57467866835729.5558259041188978.47802413835719.552591726
1189155.20182794835465.1846368761189373.36760196835361.341539219
1189512.46019149 835254.16403015 1189767.7808353835184.617735386
1189876.43879765835192.4298007341189948.10544136 835125.76315172
1190114.77205798835087.4298248741190743.10520726835104.929801539
1190790.60519183835052.4298156651191044.77178314835027.429815724
1191379.77168635835082.4297897521191585.60495546834951.596489131
1191620.60494187834837.4298551681191658.10493043834823.263191625
1191726.43824416834839.0965182931191757.27157068834917.429827571
1191841.43821284834924.929822922 1192056.4381429834689.096553057
1192138.93811175834449.9299546631192328.93804505834074.096726894
1192402.27134737833748.2634877121192713.10458428833569.930198058
1192813.93788883833599.0968531821193022.01771227833577.153464094
1193368.10438934833479.9302056881194103.96289045833563.097406954

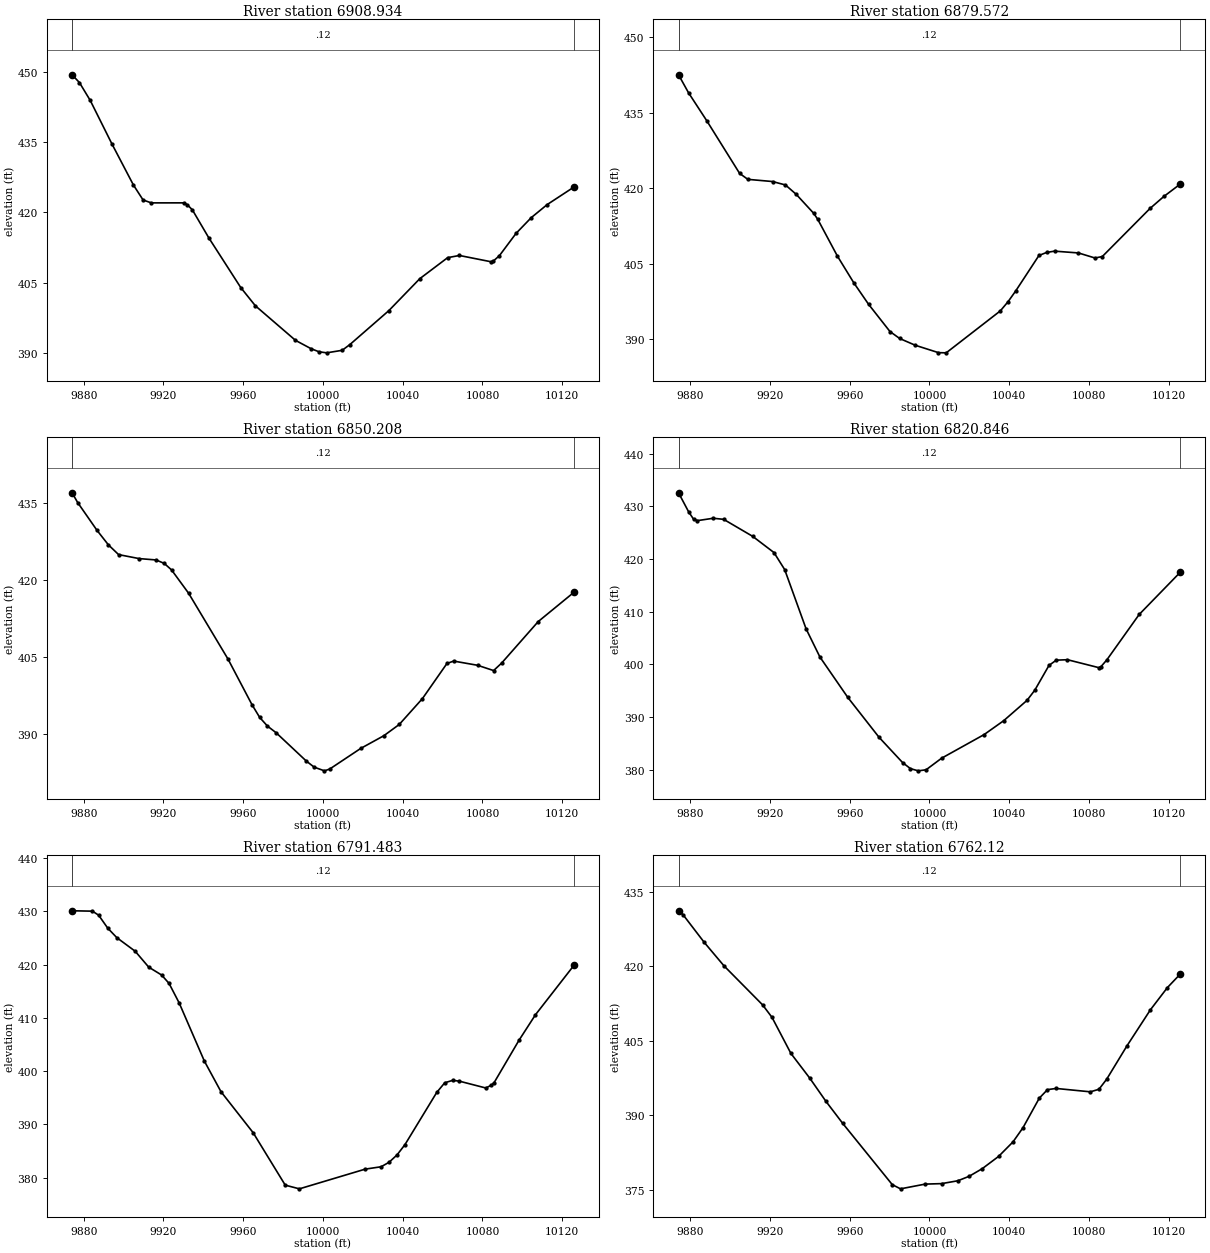
Type RM Length L Ch R = 1 ,6908.934,29.362900,29.362900,29.362900
XS GIS Cut Line= 6
1188780.19386199835995.2235481211188719.85879937835949.335664427
1188678.81535645835922.5116113471188677.11284107835921.462115568
1188631.68947033 835892.375286251188573.58419592835851.715990252
#Sta/Elev= 30
9874.166449.3129 9877.85447.6571 9883.27443.84969894.109434.60669904.948425.7978
9909.781422.61419913.903421.9913 9930.39421.99519932.046421.56589934.512 420.502
9942.756414.52949958.788403.92479966.119400.03789986.223392.67539994.062390.8891
9997.981 390.24310001.86390.009110009.65 390.54810013.55391.787110033.03398.9998
10048.61405.835310062.56410.310610068.46410.773910084.47409.422310085.45409.5811
10088.48410.714310096.89   415.5 10104.5418.8482 10112.5 421.63510125.86 425.357
#Mann= 3 , 0 , 0
9874.166    0.12       09874.166    0.12       010125.86    0.12       0
#XS Ineff= 2 , 0
       0                               0
Bank Sta=9874.166,10125.86
Exp/Cntr=0.3,0.1

Type RM Length L Ch R = 1 ,6879.572,29.363000,29.363000,29.363000
XS GIS Cut Line= 6
 1188795.8719502835969.8030388921188739.55255367835926.743612452
1188694.22350482835897.5161706411188692.52098944835896.466674861
1188642.30217403835864.8688788531188588.46223831835827.524833455
#Sta/Elev= 30
9874.171442.50859879.203438.92319888.291433.40719904.811422.92539908.941421.7465
 9921.33421.31289927.818420.6294 9933.22 418.764 9941.98 414.9989944.023413.7953
 9953.86406.5063 9962.06401.21779969.474396.95119980.223391.53189985.089390.1522
9992.897 388.80910004.56387.339210008.43387.302710035.57395.629710039.44397.4487
10043.32399.606510054.95406.633710058.82407.238510062.77407.492610074.75407.1355
10083.06 406.13210086.73 406.42410110.69415.9794 10117.6418.348310125.86420.8203
#Mann= 3 , 0 , 0
9874.171    0.12       09874.171    0.12       010125.86    0.12       0
#XS Ineff= 2 , 0
       0                               0
Bank Sta=9874.171,10125.86
Exp/Cntr=0.3,0.1

Type RM Length L Ch R = 1 ,6850.208,29.362900,29.362900,29.362900
XS GIS Cut Line= 6
1188810.67844495835945.5747166481188781.45750913 835921.30131328
1188754.92443237835901.8022610671188709.63165319835872.520729935
1188657.78516087835839.9156322311188604.02556687835802.309135647
#Sta/Elev= 30
9874.151437.01949876.959435.11929886.657429.70939892.362426.88629897.497 424.982
9907.765424.20929916.314423.94049920.386423.27089924.041422.0074  9932.6417.4678
9952.348404.66179964.359395.79739968.265393.28569972.172391.59579976.519390.3024
9991.706384.77159995.613383.600310000.75382.888810003.38383.237610018.89387.2408
10030.52389.721910038.27391.9171 10049.9396.9542 10062.2403.792710065.57404.2561
10077.58403.435110085.59402.4098 10089.6403.856210107.99411.955210125.85417.6337
#Mann= 3 , 0 , 0
9874.151    0.12       09874.151    0.12       010125.85    0.12       0
#XS Ineff= 2 , 0
       0                               0
Bank Sta=9874.151,10125.85
Exp/Cntr=0.3,0.1

Type RM Length L Ch R = 1 ,6820.846,29.363000,29.363000,29.363000
XS GIS Cut Line= 6
1188824.55440193835922.5241236981188796.12384421835897.331217146
1188770.06664861835877.2031617531188725.03980156835847.525289229
1188673.65891748835814.692378498 1188620.2804268835776.089394317
#Sta/Elev= 30
 9874.16432.57439879.251428.94269881.684427.57449883.635427.28979891.578427.7405
9896.786 427.5369911.365424.30529922.033421.2326  9927.4418.00519938.133406.7641
9945.072401.41889959.036393.76449974.753386.17859986.541 381.3929990.471380.2443
  9994.4379.82349998.329380.0233 10006.1382.217210027.43386.701810037.26389.3375
10048.95393.191610052.84395.113110059.98 399.82810063.64400.821410069.23400.9058
10084.95399.401710086.03399.5827   10089400.8807 10105.2409.483110125.85 417.511
#Mann= 3 , 0 , 0
 9874.16    0.12       0 9874.16    0.12       010125.85    0.12       0
#XS Ineff= 2 , 0
       0                               0
Bank Sta=9874.16,10125.85
Exp/Cntr=0.3,0.1

Type RM Length L Ch R = 1 ,6791.483,29.362900,29.362900,29.362900
XS GIS Cut Line= 6
1188836.84963043835901.6919567031188809.64495941835875.180157349
1188784.45713027835853.9768966521188738.91303291835821.512592399
1188685.87469914835784.7708961451188638.20922726835747.784828383
#Sta/Elev= 30
9874.159430.11429884.366430.04369887.486 429.2869892.067426.84369896.648425.0539
 9905.81422.51969912.606419.5332 9919.08418.05079922.795416.4853 9927.89412.8041
9940.523401.88769948.856396.14539964.973388.45269981.089378.59869988.181377.9073
10021.19381.607110029.17382.051810033.16382.896310037.15384.270810041.14386.2112
10057.07396.0082 10061.1397.826710065.09398.275310068.38398.127510081.68 396.841
10084.43397.364310085.84397.840410098.29405.7755 10106.6410.597410125.85419.8489
#Mann= 3 , 0 , 0
9874.159    0.12       09874.159    0.12       010125.85    0.12       0
#XS Ineff= 2 , 0
       0                               0
Bank Sta=9874.159,10125.85
Exp/Cntr=0.3,0.1

Type RM Length L Ch R = 1 , 6762.12,29.363000,29.363000,29.363000
XS GIS Cut Line= 6
1188849.03264505835883.1204031961188823.71845791835854.795216342
1188796.41059903835828.6281754961188757.55947409835798.742143932
1188709.54714312835763.1467996161188658.37528452835719.775218814
#Sta/Elev= 30
9874.174 431.1559876.421430.37059887.086424.78469896.933420.08949916.322412.2241
9921.064409.69999930.548402.44189940.032397.4504 9948.09392.81279956.537388.3603
9981.373376.04169985.512 375.1969997.881376.149510006.09376.244810014.26376.8194
10019.93  377.7210026.52379.261410034.69381.718510041.94384.649210046.95387.5061
10055.12  393.4510059.23 395.16210063.53395.399510080.73394.720110085.03395.2317
10088.92397.263410099.07403.961810110.84411.222310119.37 415.69910125.85418.4298
#Mann= 3 , 0 , 0
9874.174    0.12       09874.174    0.12       010125.85    0.12       0
#XS Ineff= 2 , 0
       0                               0
Bank Sta=9874.174,10125.85
Exp/Cntr=0.3,0.1

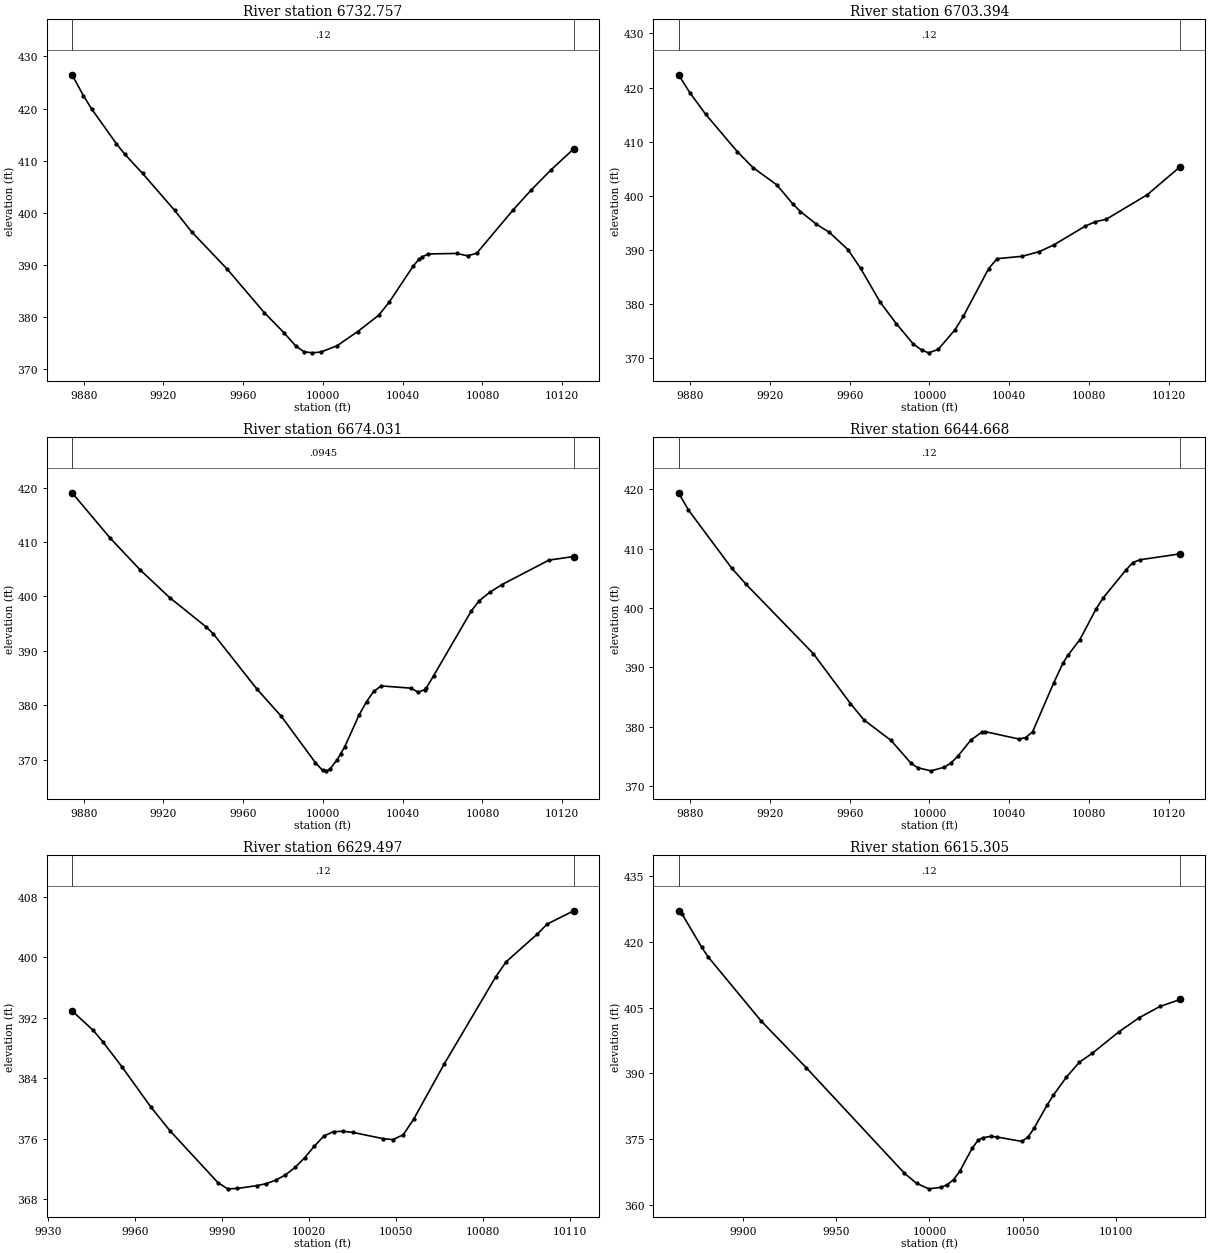
Type RM Length L Ch R = 1 ,6732.757,29.362900,29.362900,29.362900
XS GIS Cut Line= 6
1188858.74599038835866.2748277481188826.32421191835824.269097044
  1188802.756444835798.4759429621188787.02632728 835784.24706803
  1188741.955842835748.6847127011188680.66770853835689.741486229
#Sta/Elev= 30
9874.166426.4898 9879.87422.47619884.014419.91969896.447413.25239900.592411.2677
9909.515407.58859925.623400.48819934.219396.35639951.995389.22619970.536380.9162
9980.317377.08849986.355374.50229990.471373.40899994.587373.1898    9999373.3597
10006.99374.526210017.45377.278910027.91380.380810033.13382.856610045.28389.8352
10048.06  391.1110049.83391.590910052.79 392.14510066.99392.241710072.59391.7929
10077.15392.294810095.35400.578710104.46404.417710114.32408.244110125.83412.3182
#Mann= 3 , 0 , 0
9874.166    0.12       09874.166    0.12       010125.83    0.12       0
#XS Ineff= 2 , 0
       0                               0
Bank Sta=9874.166,10125.83
Exp/Cntr=0.3,0.1

Type RM Length L Ch R = 1 ,6703.394,29.363000,29.363000,29.363000
XS GIS Cut Line= 5
1188866.48307826835856.6214455581188815.25950691835780.981999145
1188794.82308801835754.4471290131188793.61777695835752.851126114
1188715.17732309835655.705639292
#Sta/Elev= 30
9874.156422.36329879.837419.05849887.761415.06379903.611408.18199911.536405.2078
9923.423 402.0419931.347398.5593 9935.31397.10299943.234394.78539949.876393.2428
9959.084390.09249965.508386.59499975.358380.33529983.404376.38879991.923372.6289
9996.064371.53799999.541371.006710004.39371.636810012.83375.265610017.04377.7692
10029.69386.548210033.91388.392310046.56388.841410054.99389.687710062.27 390.908
10077.94394.364110083.16 395.21210088.73395.684110109.27400.207410125.86405.4064
#Mann= 3 , 0 , 0
9874.156    0.12       09874.156    0.12       010125.86    0.12       0
#XS Ineff= 2 , 0
       0                               0
Bank Sta=9874.156,10125.86
Exp/Cntr=0.3,0.1

Type RM Length L Ch R = 1 ,6674.031,29.363000,29.363000,29.363000
XS GIS Cut Line= 6
1188875.25983479835849.038143217 1188850.0838336835802.326623513
1188817.80569942 835735.972801621188799.67981748835700.602428194
1188777.06510345 835661.809385061188754.98144724835628.220858108
#Sta/Elev= 30
9874.145419.04239893.236410.72959908.144404.94199923.052399.81079941.392394.4178
9945.043393.12039966.949382.96639979.122377.99039996.158369.51519999.789368.0716
10001.75367.985510003.43368.277110007.12 370.04610008.95371.162410010.81372.3259
10018.18378.290610021.87380.702810025.55382.607410029.24383.579910044.08383.1659
10047.88 382.42110051.03382.918810051.68383.110810055.48385.427210074.46397.3795
10078.26399.166710083.61400.758710089.75402.178310113.35406.676710125.85407.3416
#Mann= 3 , 0 , 0
9874.145  0.0945       09874.145  0.0945       010125.85  0.0945       0
#XS Ineff= 2 , 0
       0                               0
Bank Sta=9874.145,10125.85
Exp/Cntr=0.3,0.1

Type RM Length L Ch R = 1 ,6644.668,15.171100,15.171100,15.171100
XS GIS Cut Line= 6
1188886.45592608835846.5805855181188870.31638862 835812.19618579
1188857.29594027835776.6865077611188841.73912499835706.641745154
 1188832.1750254835675.5558238321188801.40698065835611.079217559
#Sta/Elev= 30
9874.171419.42729879.148 416.5199900.894406.70029908.143403.97539941.791392.3039
9960.404383.90289967.199381.12319980.775377.67619990.778 373.8339994.112373.0801
10000.77372.558510007.46373.165510010.81373.895610014.15374.980210020.84377.7787
10026.24379.054410027.68379.184710044.85377.922610048.28378.171810051.71  379.13
10062.29387.348810066.94 390.697 10069.4392.018110075.45394.685610083.62399.8792
10087.19401.737610098.49 406.38810102.04407.675110105.51408.134210125.82409.1341
#Mann= 3 , 0 , 0
9874.171    0.12       09874.171    0.12       010125.82    0.12       0
#XS Ineff= 2 , 0
       0                               0
Bank Sta=9874.171,10125.82
Exp/Cntr=0.3,0.1

Type RM Length L Ch R = 1 ,6629.497,14.191800,14.191800,14.191800
XS GIS Cut Line= 3
1188870.00601494835786.8924180271188855.14372784 835686.44385688
1188827.98161691835620.332303852
#Sta/Elev= 30
9938.217392.90739945.448390.35589948.764388.85279955.398 385.5199965.347380.2181
 9971.98 377.0569988.563 370.174 9991.88369.37599995.196369.427810001.83369.7947
10005.15370.058510008.46370.522210011.78371.2205 10015.1 372.20210018.41373.4819
10021.73375.016110025.05376.362510028.36376.940110031.68376.979610034.99 376.844
 10045.3376.022310048.85375.8858 10052.4376.527910055.95378.558110066.59385.9231
10084.32397.428410087.87399.392910098.51403.023910102.06404.391710111.23406.1429
#Mann= 3 , 0 , 0
9938.217    0.12       09938.217    0.12       010111.23    0.12       0
#XS Ineff= 2 , 0
       0                               0
Bank Sta=9938.217,10111.23
Exp/Cntr=0.3,0.1

Type RM Length L Ch R = 1 ,6615.305,29.363000,29.363000,29.363000
XS GIS Cut Line= 6
1188907.55627304835853.5178568281188892.53482204835818.302303285
1188883.87832292835789.2900835351188864.74447494835664.346537949
1188852.47422688835630.3232118471188835.14311921835596.098617492
#Sta/Elev= 30
9865.185427.16319866.925426.53999877.626418.84129881.192 416.5789909.476402.0326
9933.747391.34479986.517367.22639993.115364.88489999.716363.642310006.34 363.987
10009.64364.631110012.95365.725310016.26 367.63210022.88372.858810026.18374.7691
10028.66375.328610032.86375.616310036.21375.486410049.63374.478810052.98375.4661
10056.34377.576110063.15382.731910066.64385.074610073.62389.176810080.59392.5836
10087.57  394.63 10101.8399.518410112.83402.771610123.86405.3067 10134.8406.9093
#Mann= 3 , 0 , 0
9865.185    0.12       09865.185    0.12       0 10134.8    0.12       0
#XS Ineff= 2 , 0
       0                               0
Bank Sta=9865.185,10134.8
Exp/Cntr=0.3,0.1

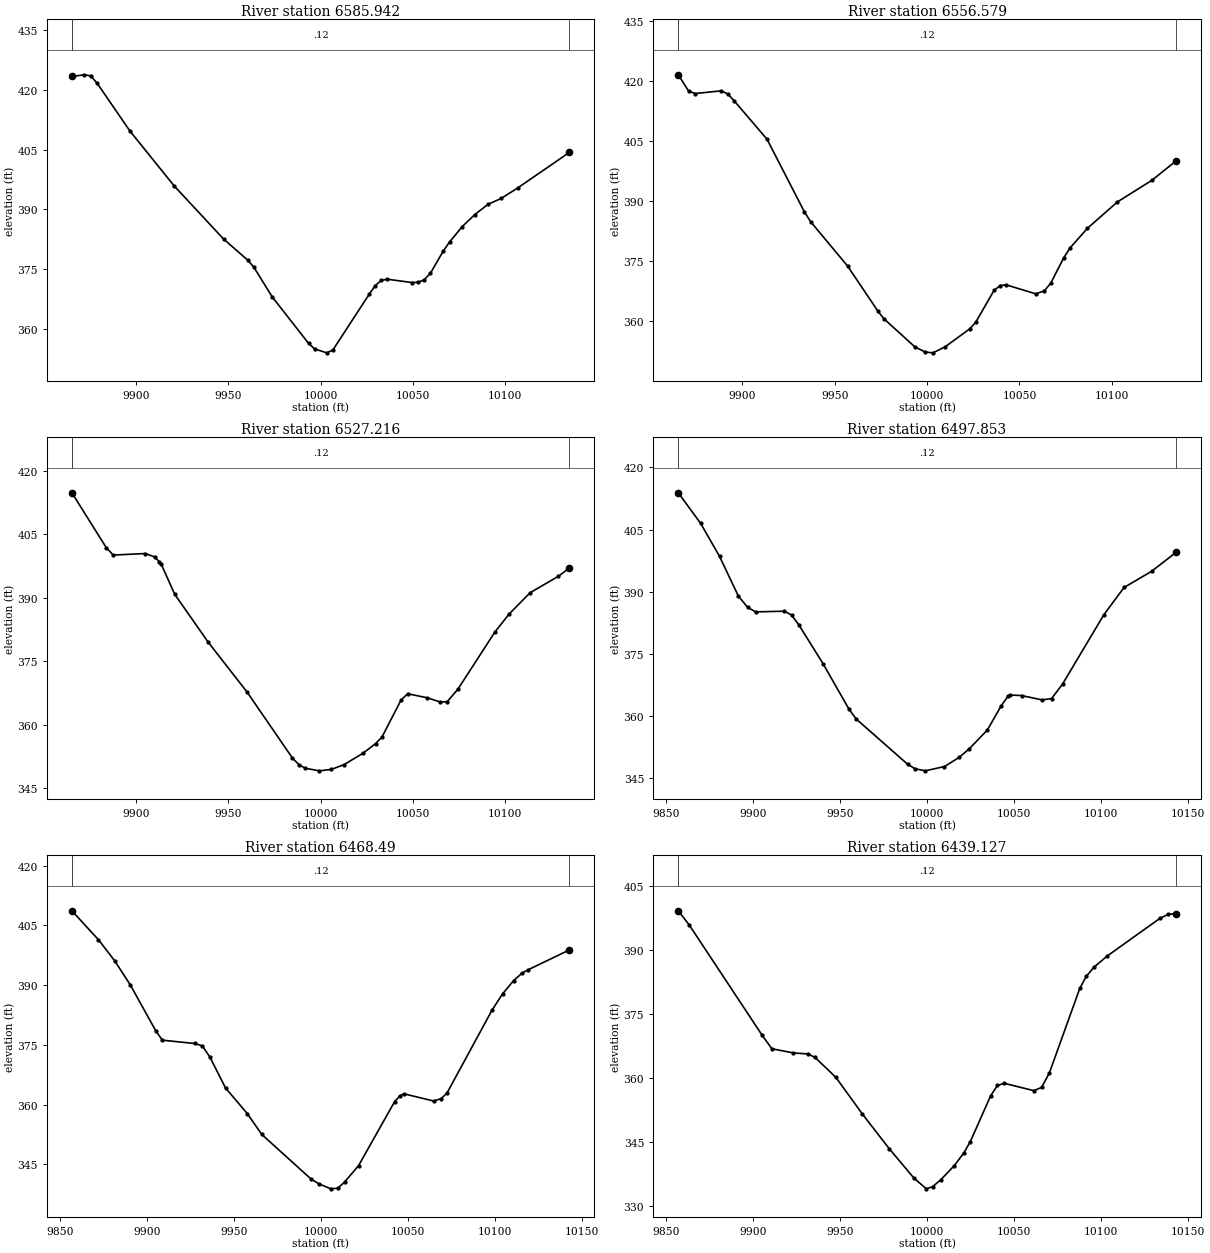
Type RM Length L Ch R = 1 ,6585.942,29.362900,29.362900,29.362900
XS GIS Cut Line= 6
1188928.73637482835854.8431262861188914.47455223835819.318710935
1188905.90360753835784.1606045711188901.24061875835669.291151935
1188891.48925054835637.8769854551188870.62925082835595.811960623
#Sta/Elev= 30
9865.226423.35679871.914423.78549875.449423.50899878.985421.61489896.661409.6731
9920.607395.88999947.425382.51899960.598377.18239963.891375.40429973.753367.9922
9993.445356.31619996.727 354.91910003.29353.940610006.57354.635710026.26368.6445
10029.57370.832810032.87372.168110036.18372.4263 10049.4 371.604 10052.7371.6448
10056.05372.274910059.48373.961710066.35379.477510069.79381.768410076.66385.6517
10083.53388.687610090.57391.2206 10097.9392.760110106.72395.361110134.74404.2994
#Mann= 3 , 0 , 0
9865.226    0.12       09865.226    0.12       010134.74    0.12       0
#XS Ineff= 2 , 0
       0                               0
Bank Sta=9865.226,10134.74
Exp/Cntr=0.3,0.1

Type RM Length L Ch R = 1 ,6556.579,29.363000,29.363000,29.363000
XS GIS Cut Line= 6
 1188958.5537765835857.0612836861188940.70619987835813.510623182
1188932.09373403835776.7657649391188935.97712779835705.497152136
1188932.12722702 835677.594351391188896.17343264835601.086528815
#Sta/Elev= 30
9865.288421.49119870.847417.44889874.392416.80879888.575417.4867 9892.12416.6798
9895.666414.93249913.343405.39859933.561387.27949936.931384.82669956.972373.7415
9973.396362.4693 9976.68360.56659993.211353.6409    9999352.277410003.16352.0886
10009.77353.601410022.98358.038410026.29359.711410036.23 367.66410039.54368.8827
10042.85369.056510058.78366.813410063.47367.565610066.97369.501710073.98 375.828
10077.49378.335410086.78383.162510103.01389.750910121.74395.168510134.67399.9553
#Mann= 3 , 0 , 0
9865.288    0.12       09865.288    0.12       010134.67    0.12       0
#XS Ineff= 2 , 0
       0                               0
Bank Sta=9865.288,10134.67
Exp/Cntr=0.3,0.1

Type RM Length L Ch R = 1 ,6527.216,29.362900,29.362900,29.362900
XS GIS Cut Line= 6
1189017.27802429835848.5423034181188997.01446809835812.058358039
1188982.15154361835780.4640399331188939.27841165835663.701658346
1188925.95102945835637.8887021871188905.57072639 835604.01227882
#Sta/Elev= 30
9865.159414.86049883.816401.87539887.569400.12499905.051400.48499909.978399.6913
9912.499398.57829913.604397.96479920.855 390.8769938.984379.5532 9960.12367.7126
9984.672352.11779988.179350.53619991.687349.67689999.311 349.07110005.71349.4004
10012.59350.517510022.92353.2216 10029.8355.526410033.24357.073110043.63 365.862
10047.18367.311310057.84366.349810064.95365.337910068.59365.438710074.33368.3558
10094.43381.9076 10102.1386.152110113.54391.220410128.86395.104710134.84397.0626
#Mann= 3 , 0 , 0
9865.159    0.12       09865.159    0.12       010134.84    0.12       0
#XS Ineff= 2 , 0
       0                               0
Bank Sta=9865.159,10134.84
Exp/Cntr=0.3,0.1

Type RM Length L Ch R = 1 ,6497.853,29.363000,29.363000,29.363000
XS GIS Cut Line= 6
1189074.59396235835824.9905860861189010.09099791 835740.21051087
1188987.53928936835712.7963916791188986.20662739835711.305079478
1188970.45038959835691.7003535261188906.01668102 835594.20973774
#Sta/Elev= 30
9856.974413.87699869.835406.47329880.672398.52149891.509388.91349896.927386.1494
9901.466385.08939917.956385.25419922.078  384.329926.201382.00259940.274372.5082
9955.058   361.6 9959.18359.22649988.786348.26189993.035347.1728    9999 346.665
10010.01347.712510018.43349.908310024.22351.985510034.67356.544110042.53362.3333
10046.47364.669610047.75364.983310054.33364.866210066.13363.809910071.56364.1355
10077.93367.674110101.52384.329310113.21390.983610129.05394.888510143.01399.4488
#Mann= 3 , 0 , 0
9856.974    0.12       09856.974    0.12       010143.01    0.12       0
#XS Ineff= 2 , 0
       0                               0
Bank Sta=9856.974,10143.01
Exp/Cntr=0.3,0.1

Type RM Length L Ch R = 1 , 6468.49,29.362900,29.362900,29.362900
XS GIS Cut Line= 6
1189113.57581189835784.1393906931189049.65767299835721.806870314
1188989.49657158835679.5772910251188969.97046928  835662.9403623
1188947.12515287835637.255716176  1188909.375379835586.749600822
#Sta/Elev= 30
9856.997408.67029872.273401.41699881.752396.03129890.562390.07449905.305378.4793
9909.049376.18589927.541375.35539931.983374.76549936.425371.87169945.309364.1985
9957.836357.74989966.144352.52439994.285 341.405    9999340.111910005.94338.8704
10009.86339.033810013.77  340.5910021.77344.693310042.51360.772810045.55362.2182
10047.94362.718510064.87360.920310069.26361.528110072.62362.930110098.65383.8542
 10104.7387.887510110.93391.165110115.66392.982910119.13393.841510142.98398.8449
#Mann= 3 , 0 , 0
9856.997    0.12       09856.997    0.12       010142.98    0.12       0
#XS Ineff= 2 , 0
       0                               0
Bank Sta=9856.997,10142.98
Exp/Cntr=0.3,0.1

Type RM Length L Ch R = 1 ,6439.127,29.363000,29.363000,29.363000
XS GIS Cut Line= 6
1189137.08042286835746.0249616211189068.68688872835690.181536723
1188998.72433314 835654.936235881188976.71329732835640.848768525
1188948.92286103835615.2402972461188913.37874898835573.074506363
#Sta/Elev= 30
9857.023399.26049863.242395.97549905.291370.01779910.787 366.9069923.206365.9209
9931.384365.69099935.474364.92959947.578360.18869962.794351.60479978.332343.4166
9992.392336.58739999.557334.050810003.11334.552610007.76336.141510015.65339.5122
10021.15342.508510024.83345.129710036.51355.870310040.41358.2918 10044.3358.7976
10061.32357.080610065.78357.840410070.25361.236910087.78 381.11410091.48383.8908
10095.77385.984210103.41388.631410133.95397.536510138.68398.441610142.93398.5932
#Mann= 3 , 0 , 0
9857.023    0.12       09857.023    0.12       010142.93    0.12       0
#XS Ineff= 2 , 0
       0                               0
Bank Sta=9857.023,10142.93
Exp/Cntr=0.3,0.1

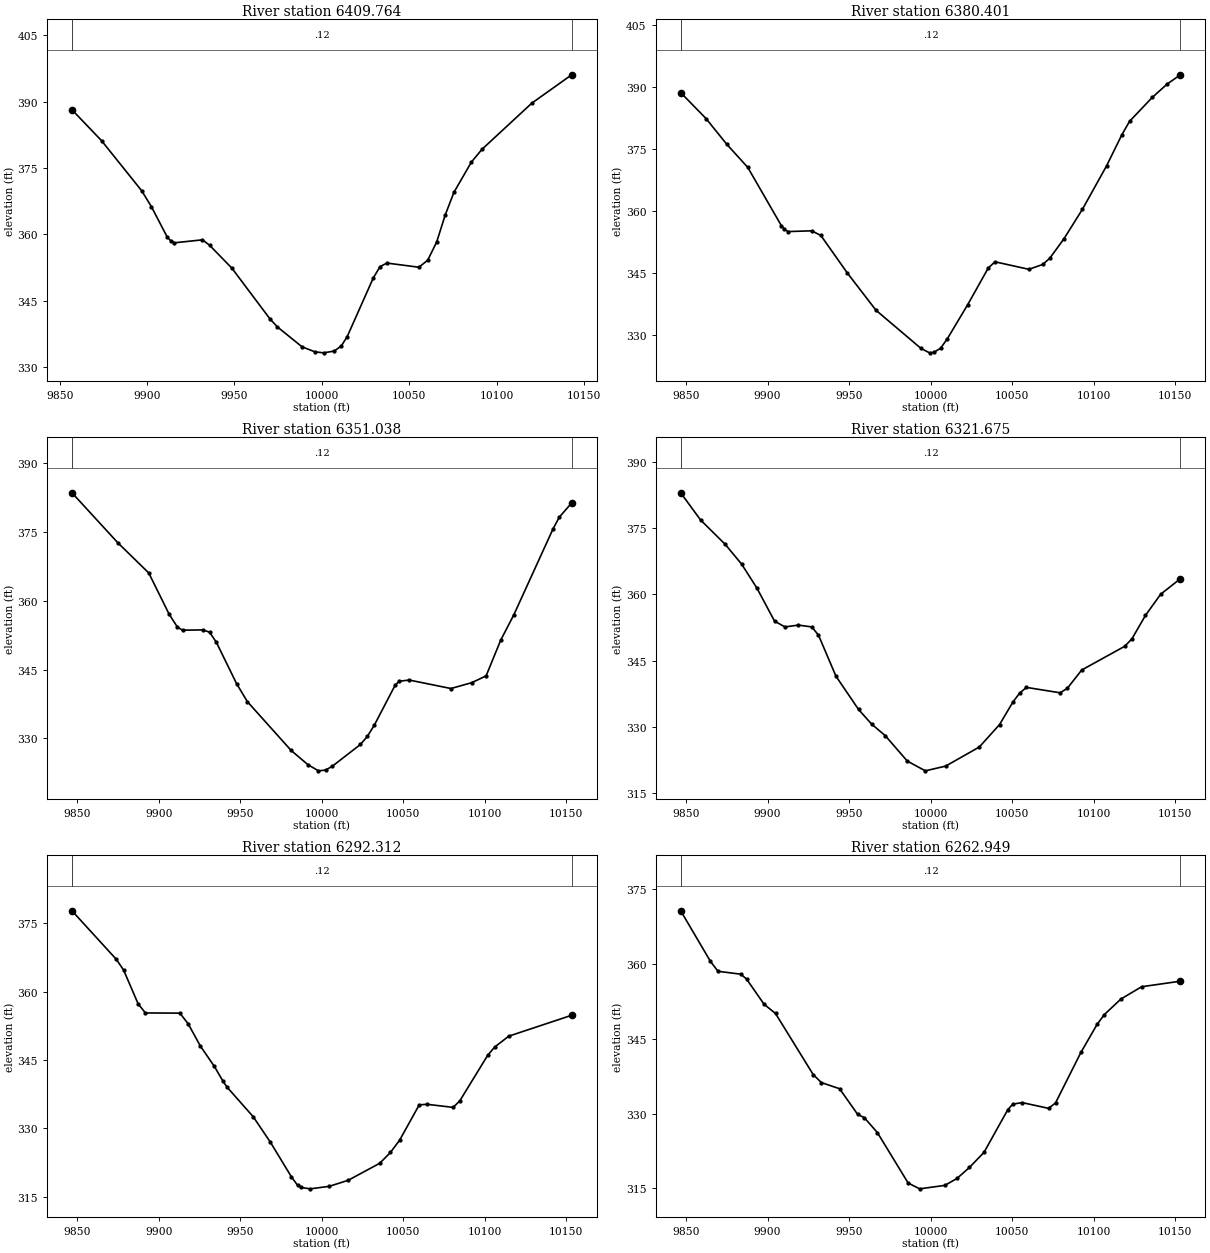
Type RM Length L Ch R = 1 ,6409.764,29.362900,29.362900,29.362900
XS GIS Cut Line= 6
1189148.71471331835716.6272966391189082.64191882835665.751435995
1189007.44523137835625.3923439211188983.60975084835609.968148937
1188952.54301571835583.1286387581188919.97485474835548.298772706
#Sta/Elev= 30
9856.997388.16439873.918381.18079896.838369.89399902.403 366.3059911.512359.3993
9913.685358.50259915.545358.10219931.678 358.7789935.711357.56559948.491352.3855
9970.341340.89119974.545339.10719988.683334.59549996.004333.4763   10001333.2452
10007.08 333.64810011.08334.793710014.44336.857710029.38350.126410033.29352.7195
 10037.2353.5264 10055.5352.589810060.52354.146110065.68358.261410070.56364.3558
10075.58369.512110085.61376.3683 10091.7379.255810120.13389.649910142.97396.0673
#Mann= 3 , 0 , 0
9856.997    0.12       09856.997    0.12       010142.97    0.12       0
#XS Ineff= 2 , 0
       0                               0
Bank Sta=9856.997,10142.97
Exp/Cntr=0.3,0.1

Type RM Length L Ch R = 1 ,6380.401,29.363000,29.363000,29.363000
XS GIS Cut Line= 6
1189167.32547817835704.7341243381189128.94595804835672.802266639
1189055.26470255835620.0058555511188993.60835894835571.356155628
 1188963.7900665 835545.348714071188929.87513709835511.482021757
#Sta/Elev= 30
9846.695388.74259862.223382.47689875.026376.2152 9887.83370.65819908.488356.5323
9910.171355.75589912.524355.12489927.069 355.3049932.702354.1789 9948.85345.1524
9966.499336.0969 9994.15326.85029999.362 325.78710002.02325.900310006.18326.9109
10010.35329.228310022.85337.480610035.35346.268510039.52347.810610060.35345.9922
10068.81347.163210073.16348.676110081.87 353.40110093.19360.519710107.97371.0036
10117.25 378.44610122.07381.784710135.98387.559810145.25390.839810153.31393.0546
#Mann= 3 , 0 , 0
9846.695    0.12       09846.695    0.12       010153.31    0.12       0
#XS Ineff= 2 , 0
       0                               0
Bank Sta=9846.695,10153.31
Exp/Cntr=0.3,0.1

Type RM Length L Ch R = 1 ,6351.038,29.363000,29.363000,29.363000
XS GIS Cut Line= 6
1189184.76155713835686.3852025221189148.74750341835655.861901315
1189076.77043458835600.3425143911189064.54009692835589.714619527
1188991.30317199835528.6630808131188949.68498908835489.768719687
#Sta/Elev= 30
9846.686383.59549874.826372.6789 9893.79366.09319906.224357.1398 9911.31354.3013
9914.511353.58529926.941353.65869931.085353.15599935.228350.99079947.659341.9339
9954.284337.99449981.142327.33479991.429324.2301 9997.95322.876710002.32323.0443
10006.54323.911810023.68328.634810027.95330.418110032.22332.863910045.03341.6165
10047.53  342.4410053.58342.7059 10079.2 340.85210092.02342.137410100.78343.6074
10109.76351.418310117.83356.968410141.86375.711210145.68378.252510153.31381.3861
#Mann= 3 , 0 , 0
9846.686    0.12       09846.686    0.12       010153.31    0.12       0
#XS Ineff= 2 , 0
       0                               0
Bank Sta=9846.686,10153.31
Exp/Cntr=0.3,0.1

Type RM Length L Ch R = 1 ,6321.675,29.362900,29.362900,29.362900
XS GIS Cut Line= 6
1189204.04516862835662.9319972691189154.24786849835620.429842478
1189084.73676677835568.382019188 1189083.1929063835567.110604682
1189021.26376709835519.6588330141188965.88357799 835470.16100313
#Sta/Elev= 30
9846.693382.98869858.902376.83029873.969371.34519884.076366.84949893.409361.4585
9904.291353.94849910.662352.64929918.934353.05719927.132352.6456 9931.23350.7892
9941.953341.50119955.822333.97439963.848330.66049972.216328.04539985.744 322.293
9996.808320.093310009.24321.163110029.91325.480710042.31330.551310050.58335.6844
10054.71337.697310058.84338.966110079.54337.743210083.94338.781310092.74342.8974
10119.14348.269910123.54349.948510131.83355.240810141.14360.0261 10153.3363.5632
#Mann= 3 , 0 , 0
9846.693    0.12       09846.693    0.12       0 10153.3    0.12       0
#XS Ineff= 2 , 0
       0                               0
Bank Sta=9846.693,10153.3
Exp/Cntr=0.3,0.1

Type RM Length L Ch R = 1 ,6292.312,29.363000,29.363000,29.363000
XS GIS Cut Line= 6
1189221.36276588835636.4985131631189186.61390136835604.543248496
1189155.55245739835579.5963580131189070.92645086835524.974898593
1189040.70352296835503.2719193441188979.61125613835449.221321778
#Sta/Elev= 30
9846.691377.7259 9873.92367.05849878.377364.70799887.291357.29559891.749355.2996
9912.909355.25569918.002 352.9069925.533347.99829933.938343.62999939.459340.2539
9941.934 338.9739957.925332.50429968.396326.94789981.339319.31859985.198317.4285
9987.098 316.9989992.915316.686610004.52317.236310016.13318.554710035.52322.2952
10042.07324.6659 10047.7327.348910059.76335.122310064.57335.245410080.59334.5649
10084.68336.019310101.75345.992310106.02347.799510114.67350.196610153.31354.7908
#Mann= 3 , 0 , 0
9846.691    0.12       09846.691    0.12       010153.31    0.12       0
#XS Ineff= 2 , 0
       0                               0
Bank Sta=9846.691,10153.31
Exp/Cntr=0.3,0.1

Type RM Length L Ch R = 1 ,6262.949,29.362900,29.362900,29.362900
XS GIS Cut Line= 6
1189233.36733518835612.0871932171189169.63654816835552.863195931
 1189141.3129278835532.6390883341189067.44299131 835488.75133015
1189029.70744856835457.6267917591188993.91471914835422.978459811
#Sta/Elev= 30
9846.712370.58269864.924360.47479869.594358.46799883.605357.89049887.131356.9132
9897.888351.86399904.883350.02459927.982337.80939932.997336.19829944.193334.9592
9955.298 329.8219959.329329.18539967.392326.17549986.269316.0814 9993.31314.9232
10008.76 315.61410016.25317.011810023.87319.209310032.78322.221910047.43330.7963
10050.47331.864610056.14332.190510072.39331.034610076.65332.111110092.23342.2243
10102.16347.842410106.63349.811910116.77352.912310129.46355.376910153.29356.4889
#Mann= 3 , 0 , 0
9846.712    0.12       09846.712    0.12       010153.29    0.12       0
#XS Ineff= 2 , 0
       0                               0
Bank Sta=9846.712,10153.29
Exp/Cntr=0.3,0.1

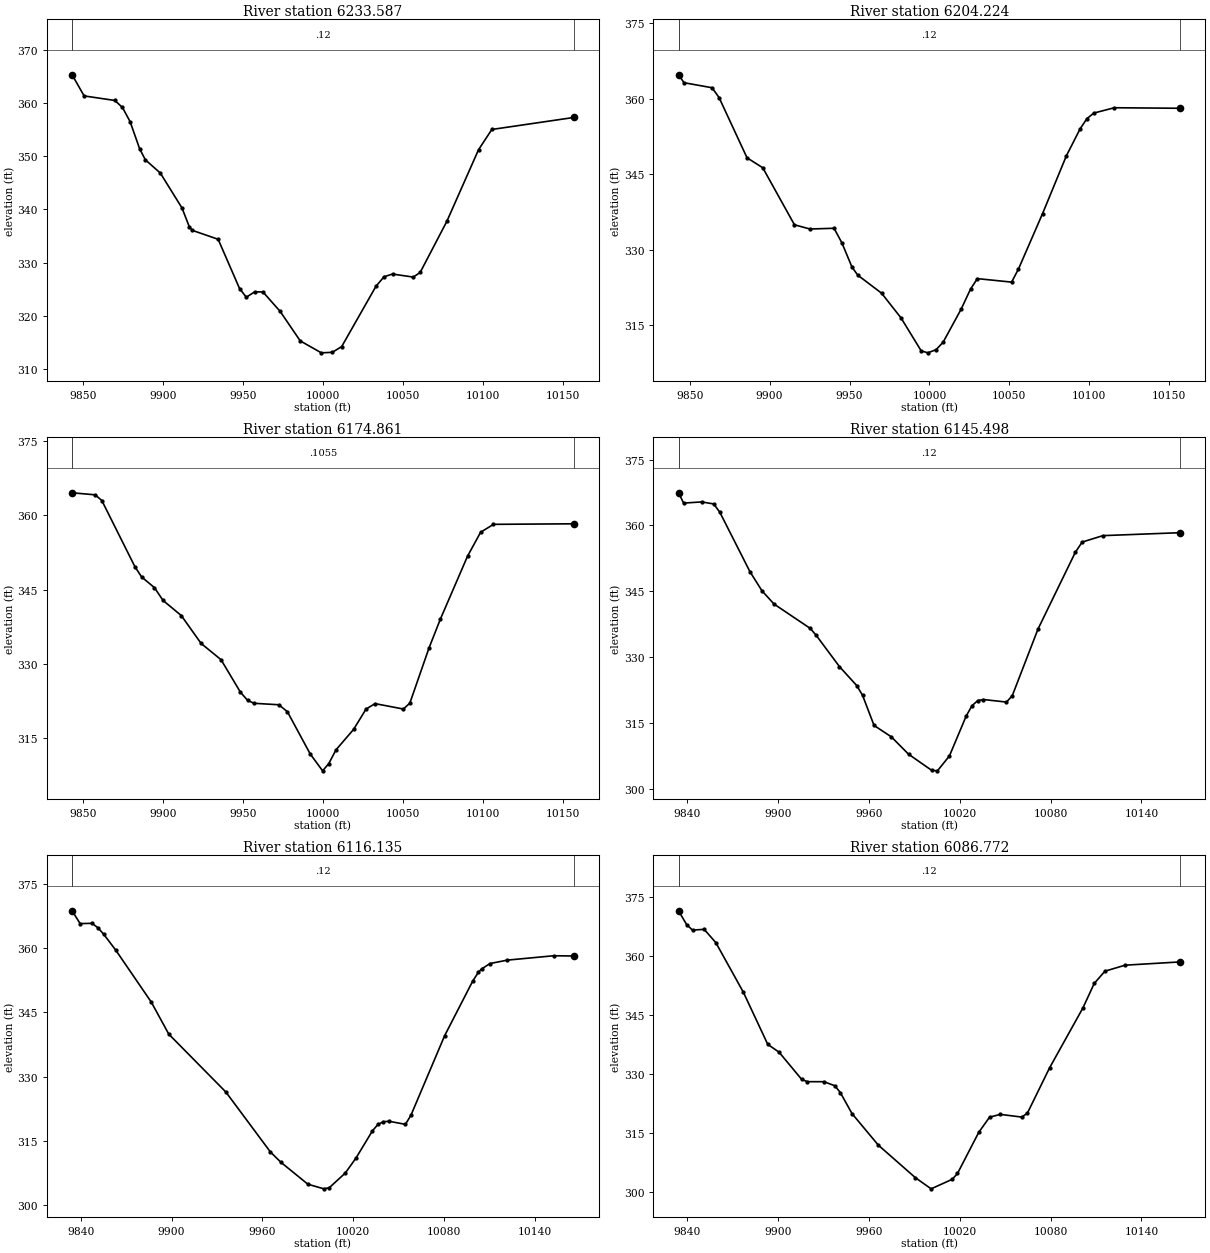
Type RM Length L Ch R = 1 ,6233.587,29.363000,29.363000,29.363000
XS GIS Cut Line= 6
  1189242.586331835597.3130991251189207.73153566 835560.26878611
1189170.63324361835525.0344874051189106.84465814835476.438483618
 1189077.4098023835451.1725298851189012.59700496835384.753396313
#Sta/Elev= 30
9843.047365.29799850.601361.32259869.752 360.474 9874.54359.16489879.327356.5066
9885.375351.33699888.903349.31519898.228346.83629911.802340.26989916.327336.7745
9918.233336.06129934.425334.37769947.816325.12399952.058323.48519957.322324.5115
9962.499324.46329973.264320.80959985.793315.2749    9999313.034710005.84313.1338
10011.72314.214910033.16 325.54610038.19327.3314 10043.5327.847410056.48327.2724
 10060.8328.1378 10077.5337.758210097.32351.212310105.64355.017510156.95357.2765
#Mann= 3 , 0 , 0
9843.047    0.12       09843.047    0.12       010156.95    0.12       0
#XS Ineff= 2 , 0
       0                               0
Bank Sta=9843.047,10156.95
Exp/Cntr=0.3,0.1

Type RM Length L Ch R = 1 ,6204.224,29.362900,29.362900,29.362900
XS GIS Cut Line= 5
1189252.62707226835588.7612868761189149.34070252835471.885237035
1189147.99277855835470.4077049861189141.55260052 835463.15226338
1189047.44655982835351.168118098
#Sta/Elev= 30
9843.025364.74689846.484363.16639863.997362.16939868.375360.22059885.889348.2366
9895.732346.2585 9915.55334.91839925.294334.07999940.322  334.239945.277331.2969
9951.564326.50119955.185324.89959970.049321.32669982.213316.41139994.821 309.869
    9999309.461110004.14310.088810008.53311.553410019.79318.116310025.72322.1349
10029.99324.216210051.43323.522410055.72326.133210070.79337.150610085.71 348.652
10094.29354.005510098.57356.035610102.86357.132410115.71358.192710156.98358.0869
#Mann= 3 , 0 , 0
9843.025    0.12       09843.025    0.12       010156.98    0.12       0
#XS Ineff= 2 , 0
       0                               0
Bank Sta=9843.025,10156.98
Exp/Cntr=0.3,0.1

Type RM Length L Ch R = 1 ,6174.861,29.363000,29.363000,29.363000
XS GIS Cut Line= 6
1189265.61609956835581.227649124 1189197.5998947835493.010874084
1189173.37419053 835455.60796192 1189172.3567319835453.886108864
1189146.58553873835413.3571830391189084.08974658835325.348473688
#Sta/Elev= 30
9843.044364.58399857.517364.1683 9861.66363.01619882.374349.61219886.516347.5606
9894.612 345.3649899.985 342.7799911.373339.72939923.801334.0735 9936.23330.7952
9948.344324.22949952.801322.57469956.802321.96899972.438321.66559977.768320.2546
9991.982311.7353 9999.78 308.29110003.64309.753310008.16312.540810019.19316.6902
10026.97320.802210032.62321.896310050.34320.803810054.37322.004410066.44333.2439
10073.49339.030610090.49351.775410098.63356.585410106.68358.194810156.97358.3036
#Mann= 3 , 0 , 0
9843.044  0.1055       09843.044  0.1055       010156.97  0.1055       0
#XS Ineff= 2 , 0
       0                               0
Bank Sta=9843.044,10156.97
Exp/Cntr=0.3,0.1

Type RM Length L Ch R = 1 ,6145.498,29.362900,29.362900,29.362900
XS GIS Cut Line= 6
1189287.66647273835579.0856557521189234.99562012 835502.58224442
1189198.65353693835440.6701663111189197.63607831835438.948313255
1189159.03877629835372.9069784191189111.33007116835298.731158202
#Sta/Elev= 30
9834.328367.45589837.677365.10299849.626365.37079857.593364.90559861.576363.0218
9881.492 349.4539889.458345.08249897.425342.06649921.324336.51439925.307 334.911
 9940.61327.80129952.023 323.4729955.827321.27419963.436314.38759974.849 311.786
9986.262307.810810001.48304.148410005.28304.0291 10013.2307.420310024.28316.5257
10028.08318.869410031.88320.049810035.68320.294910050.88 319.71610054.68321.1392
10071.72336.382210096.37353.885610100.89356.214610114.57357.680410165.69358.3556
#Mann= 3 , 0 , 0
9834.328    0.12       09834.328    0.12       010165.69    0.12       0
#XS Ineff= 2 , 0
       0                               0
Bank Sta=9834.328,10165.69
Exp/Cntr=0.3,0.1

Type RM Length L Ch R = 1 ,6116.135,29.363000,29.363000,29.363000
XS GIS Cut Line= 6
1189303.39941481835570.9505689631189270.92642908835521.004526949
1189251.20565552835486.3865558891189233.68893678835450.318059983
1189199.69146984835370.9785098731189147.37008268835279.431857854
#Sta/Elev= 30
9834.333368.79969839.659365.79819847.486365.86539851.399 364.8259855.313363.2731
9863.139359.60219886.619347.44029898.202339.92369935.885326.38229965.328312.3383
9972.358 309.8999990.091304.793610000.67 303.72110004.18303.985110014.75307.4174
10021.84310.942610032.71317.313310036.33318.801610039.96319.426710043.58319.5334
10054.45318.821210058.07320.919410080.35339.564310098.97 352.395 10102.7 354.432
10104.84355.199410110.29356.450310121.75357.250910152.32 358.27310165.68358.2209
#Mann= 3 , 0 , 0
9834.333    0.12       09834.333    0.12       010165.68    0.12       0
#XS Ineff= 2 , 0
       0                               0
Bank Sta=9834.333,10165.68
Exp/Cntr=0.3,0.1

Type RM Length L Ch R = 1 ,6086.772,29.362900,29.362900,29.362900
XS GIS Cut Line= 6
1189325.41313997835564.506790599 1189279.0220417835484.074739863
1189263.44766809835449.0928216921189229.97603902835360.697487818
1189210.53142253835321.4784286891189180.08353217835267.655132459
#Sta/Elev= 30
 9834.33371.38699839.706367.86249843.554  366.489851.251366.66929858.947363.3058
9877.165350.67489893.254337.44929900.704335.47069915.603328.57629919.328327.9747
9930.384327.96529937.567326.93369941.158325.21039948.865319.87439966.274311.8463
9990.685303.598810001.13300.751710015.05303.172810018.53304.651910032.59315.1137
10039.71318.952710046.82319.666410061.07318.974910064.74320.021810079.38331.5129
10101.35346.702510108.82  352.9210115.88356.039210129.21357.567610165.68358.4001
#Mann= 3 , 0 , 0
 9834.33    0.12       0 9834.33    0.12       010165.68    0.12       0
#XS Ineff= 2 , 0
       0                               0
Bank Sta=9834.33,10165.68
Exp/Cntr=0.3,0.1