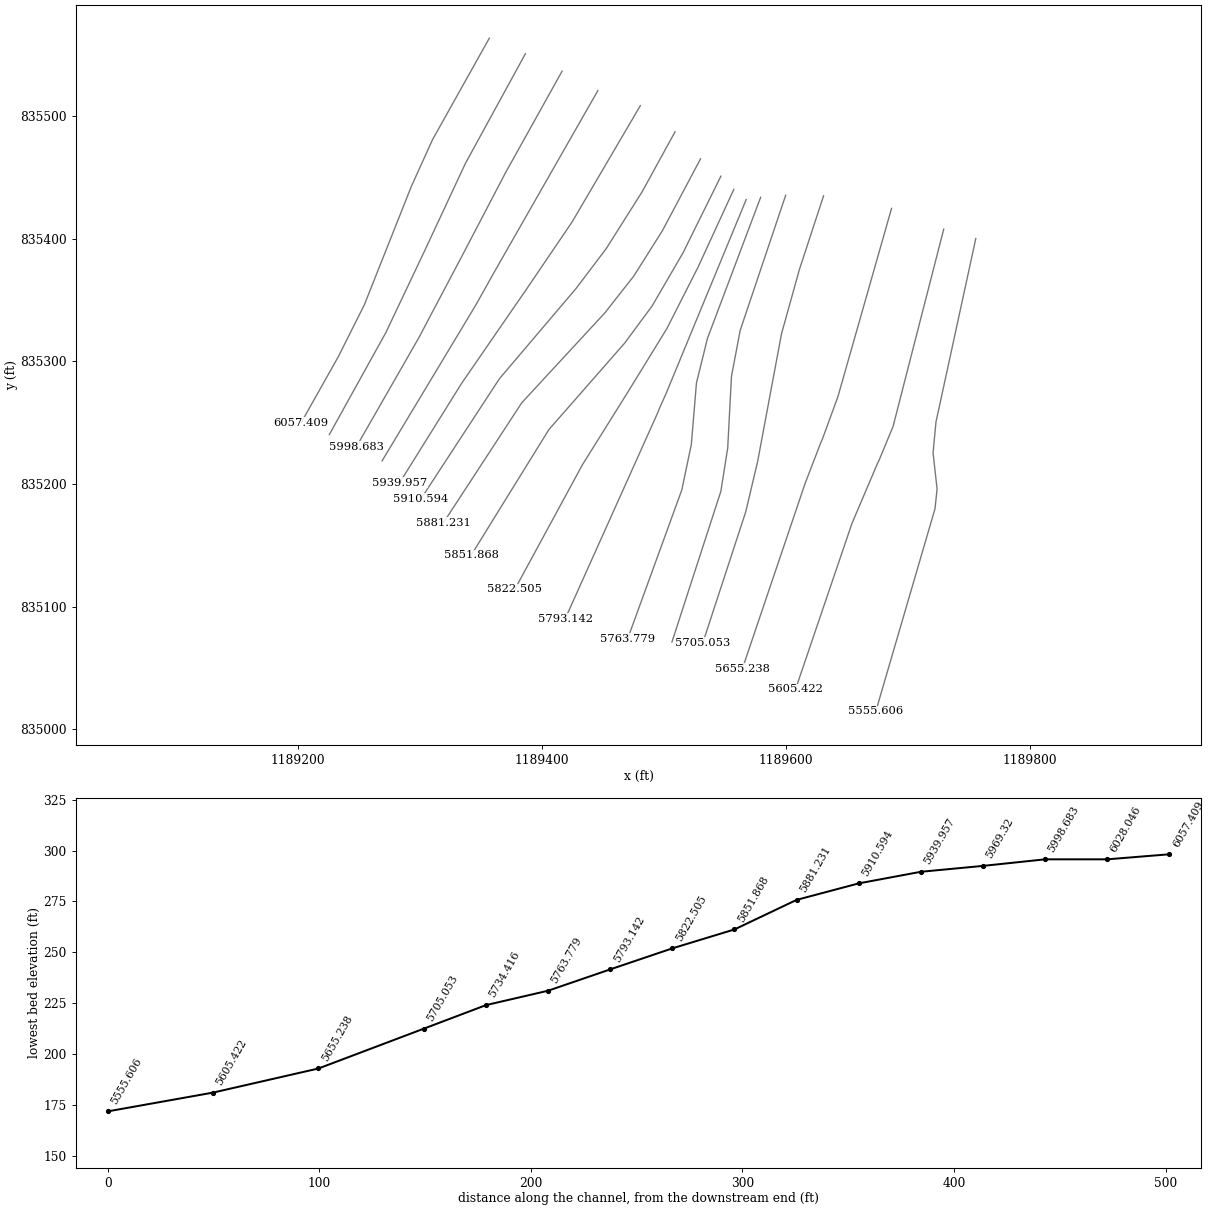
HEC-RAS study 79_ras.prj: 79

--- 79_ras.g01 (geometry) --- (continued)

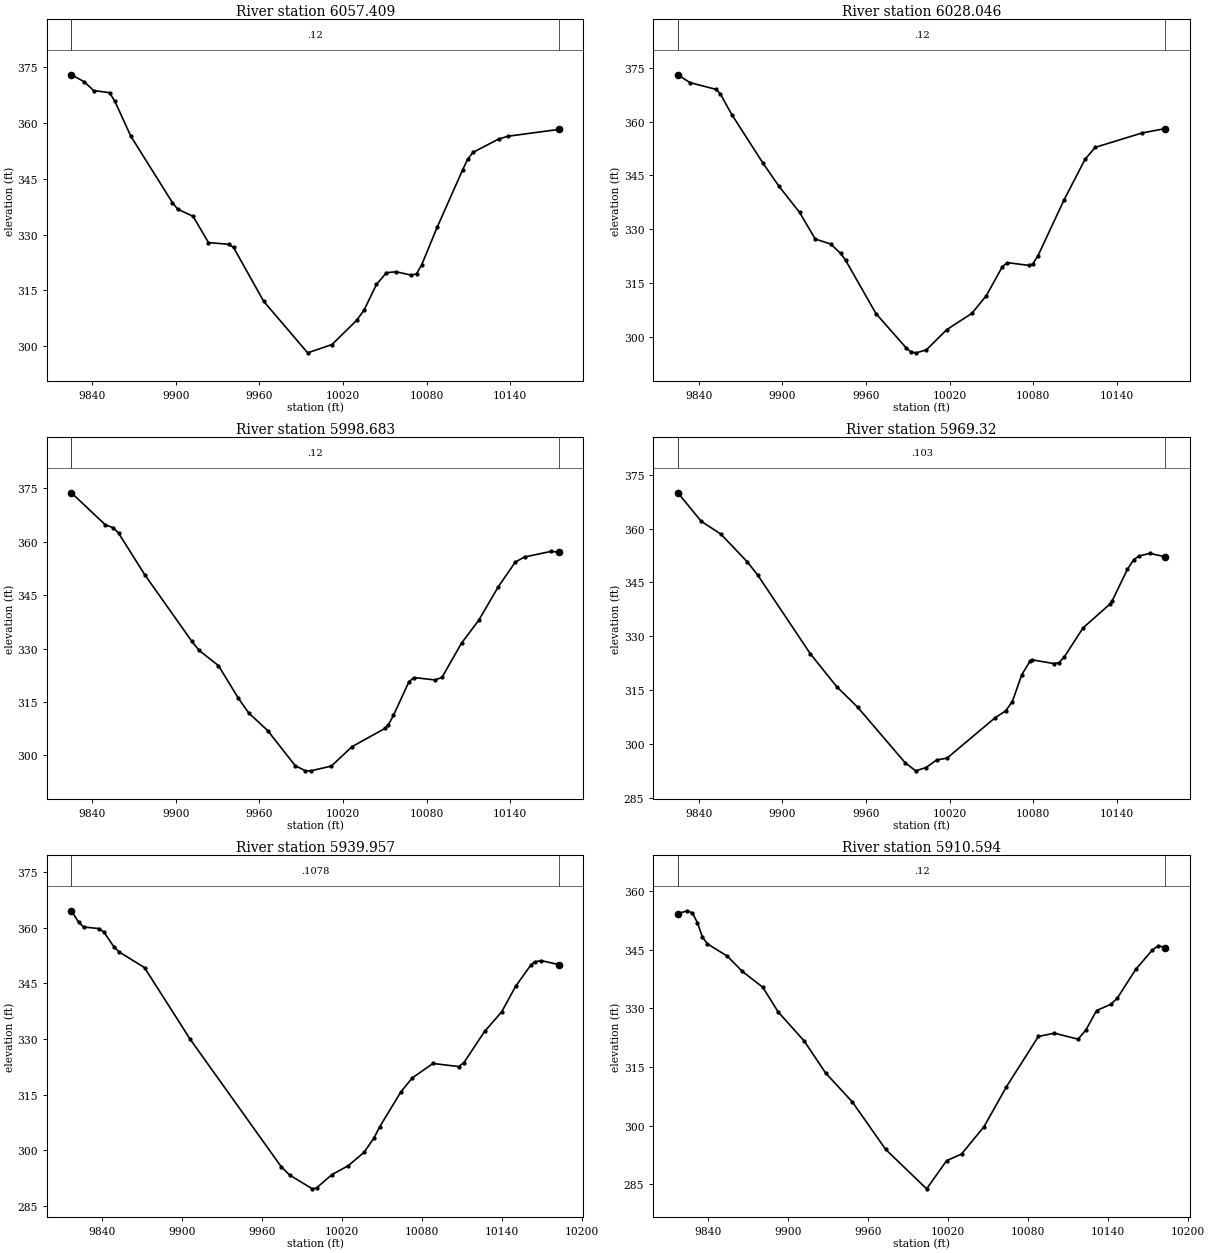
Type RM Length L Ch R = 1 ,6057.409,29.363000,29.363000,29.363000
XS GIS Cut Line= 6
1189356.99417461835563.8328825881189310.45048305835480.959900351
1189293.03641424 835442.602445951189254.66008585835346.253946965
1189233.34597932835303.9458635731189202.98698865835250.161841693
#Sta/Elev= 30
9824.965372.97149834.286371.08039840.954368.72889852.397368.15119856.212365.8188
9867.656356.44599897.491338.60079901.207336.84579912.354334.89869923.397327.8289
9937.809327.38649941.412326.51649963.009312.0451 9994.61298.176310012.11300.4167
10029.69306.899310035.06309.658710043.99316.560510051.15319.7534 10058.3319.9721
10069.11319.056410072.79319.474710076.46321.844410087.48331.901810105.85347.3973
10109.52350.2913 10113.2352.079110131.71355.694710138.38356.437910175.04358.2839
#Mann= 3 , 0 , 0
9824.965    0.12       09824.965    0.12       010175.04    0.12       0
#XS Ineff= 2 , 0
       0                               0
Bank Sta=9824.965,10175.04
Exp/Cntr=0.3,0.1

Type RM Length L Ch R = 1 ,6028.046,29.363000,29.363000,29.363000
XS GIS Cut Line= 6
1189386.60192567835551.252209903 1189337.4120415835461.621550535
1189306.97802258835396.6010515351189306.15041669835394.780318581
1189272.37702722835323.7906974521189226.01460279835240.387724666
#Sta/Elev= 30
9824.968372.98749833.789370.79489852.501368.92539855.476367.68599863.729361.9103
9886.183348.3659 9897.41342.0819 9912.38334.73189923.607327.3383 9934.59 325.955
9941.835323.35089945.458321.39919967.192306.61229988.927297.05979992.549295.8741
9996.172295.695610003.41296.528810017.95302.126810036.11306.683410046.46311.6118
10057.91319.631210061.54  320.77   10077320.002610079.71320.382410083.47322.6664
10102.24338.222510117.25349.461610124.57352.813510158.34356.826910175.04358.0436
#Mann= 3 , 0 , 0
9824.968    0.12       09824.968    0.12       010175.04    0.12       0
#XS Ineff= 2 , 0
       0                               0
Bank Sta=9824.968,10175.04
Exp/Cntr=0.3,0.1

Type RM Length L Ch R = 1 ,5998.683,29.362900,29.362900,29.362900
XS GIS Cut Line= 6
1189416.63693021835536.970817304 1189370.2394109835453.979445934
 1189333.5784647835384.031267229 1189332.6258984835382.272683296
1189299.04476054835318.9573216161189248.01779348835230.196661511
#Sta/Elev= 30
9824.946373.69549849.342364.70349855.031363.9037 9858.79362.40069877.584350.7413
9911.413332.03619916.575329.50959930.533325.21769944.875316.04249952.283311.9209
 9965.87306.99479985.621297.14989993.029295.70049996.733295.695210011.59297.0268
10026.45 302.48110050.17307.605410052.44 308.55210056.16311.2267 10067.3320.6919
10071.01321.867310086.12321.187710091.01321.917410105.04331.521510117.34337.8875
10131.53347.382610143.67354.261310150.26355.683410169.37357.256110175.05356.9944
#Mann= 3 , 0 , 0
9824.946    0.12       09824.946    0.12       010175.05    0.12       0
#XS Ineff= 2 , 0
       0                               0
Bank Sta=9824.946,10175.05
Exp/Cntr=0.3,0.1

Type RM Length L Ch R = 1 , 5969.32,29.363000,29.363000,29.363000
XS GIS Cut Line= 5
1189445.91106249835521.0759093851189359.39707464835370.046186854
1189358.44450834835368.287602921 1189346.1200387835346.349952619
1189269.17984243835218.876934568
#Sta/Elev= 30
9824.946369.99519841.787362.03049855.797358.4938 9874.79350.74869882.263347.0788
9920.073325.10639938.978315.96119954.102310.19219988.131294.73919995.693292.4725
10003.22293.401710010.74295.493910018.27 296.02510052.42307.179210060.28309.1779
10065.11311.770910071.78319.175310077.81323.087710079.44323.413510094.77322.3918
 10098.6322.622110102.43324.248310115.91332.353210134.95338.889310136.92339.9561
10147.65348.608610152.25351.347410156.08 352.36210163.75353.096210175.06352.1455
#Mann= 3 , 0 , 0
9824.946   0.103       09824.946   0.103       010175.06   0.103       0
#XS Ineff= 2 , 0
       0                               0
Bank Sta=9824.946,10175.06
Exp/Cntr=0.3,0.1

Type RM Length L Ch R = 1 ,5939.957,29.362900,29.362900,29.362900
XS GIS Cut Line= 6
1189480.69185437835508.7791898051189424.82982715835413.901239322
1189384.42679499835354.5625805211189383.25324449835352.943080835
1189334.45645357835282.3519107561189283.48528402835200.891210211
#Sta/Elev= 30
9817.111364.60169822.483 361.5589826.291360.22399837.713359.8088 9841.52358.8713
9849.134354.82369852.942353.51239871.978349.25899906.243329.9345 9974.58295.5147
9980.765 293.3119997.898289.5773   10001289.817610012.62293.435710024.58295.7595
10036.55299.3939   10044303.232110048.51306.387310064.46315.832410072.85319.5106
10088.35323.4044 10107.7322.570210111.57323.632510127.05332.031710139.88337.3202
10150.27344.179110161.88350.024910164.62350.823710169.62 351.15210182.91350.0566
#Mann= 3 , 0 , 0
9817.111  0.1078       09817.111  0.1078       010182.91  0.1078       0
#XS Ineff= 2 , 0
       0                               0
Bank Sta=9817.111,10182.91
Exp/Cntr=0.3,0.1

Type RM Length L Ch R = 1 ,5910.594,29.363000,29.363000,29.363000
XS GIS Cut Line= 6
1189509.17906862835487.5320676651189482.14769301835438.454430712
1189452.79654039835392.1628873221189428.06518034835359.571605589
1189365.38061035 835286.037944361189301.04917065835187.930210398
#Sta/Elev= 30
9817.118354.16369824.366354.89599828.111 354.3259831.857351.80539835.603348.1518
9839.348346.4378 9854.33343.28159865.567  339.399880.824335.37899892.479329.0212
9911.902321.6421 9927.96313.47279948.003306.08969972.953293.975510003.75283.8829
10018.71291.070410029.96292.787710046.74299.729710063.53309.911610087.58322.8054
10099.56323.632210117.38322.106810123.25324.474110131.18  329.4110141.88331.0183
10146.64332.529510160.52339.903610172.94344.828310177.55346.0083 10182.9345.4304
#Mann= 3 , 0 , 0
9817.118    0.12       09817.118    0.12       0 10182.9    0.12       0
#XS Ineff= 2 , 0
       0                               0
Bank Sta=9817.118,10182.9
Exp/Cntr=0.3,0.1

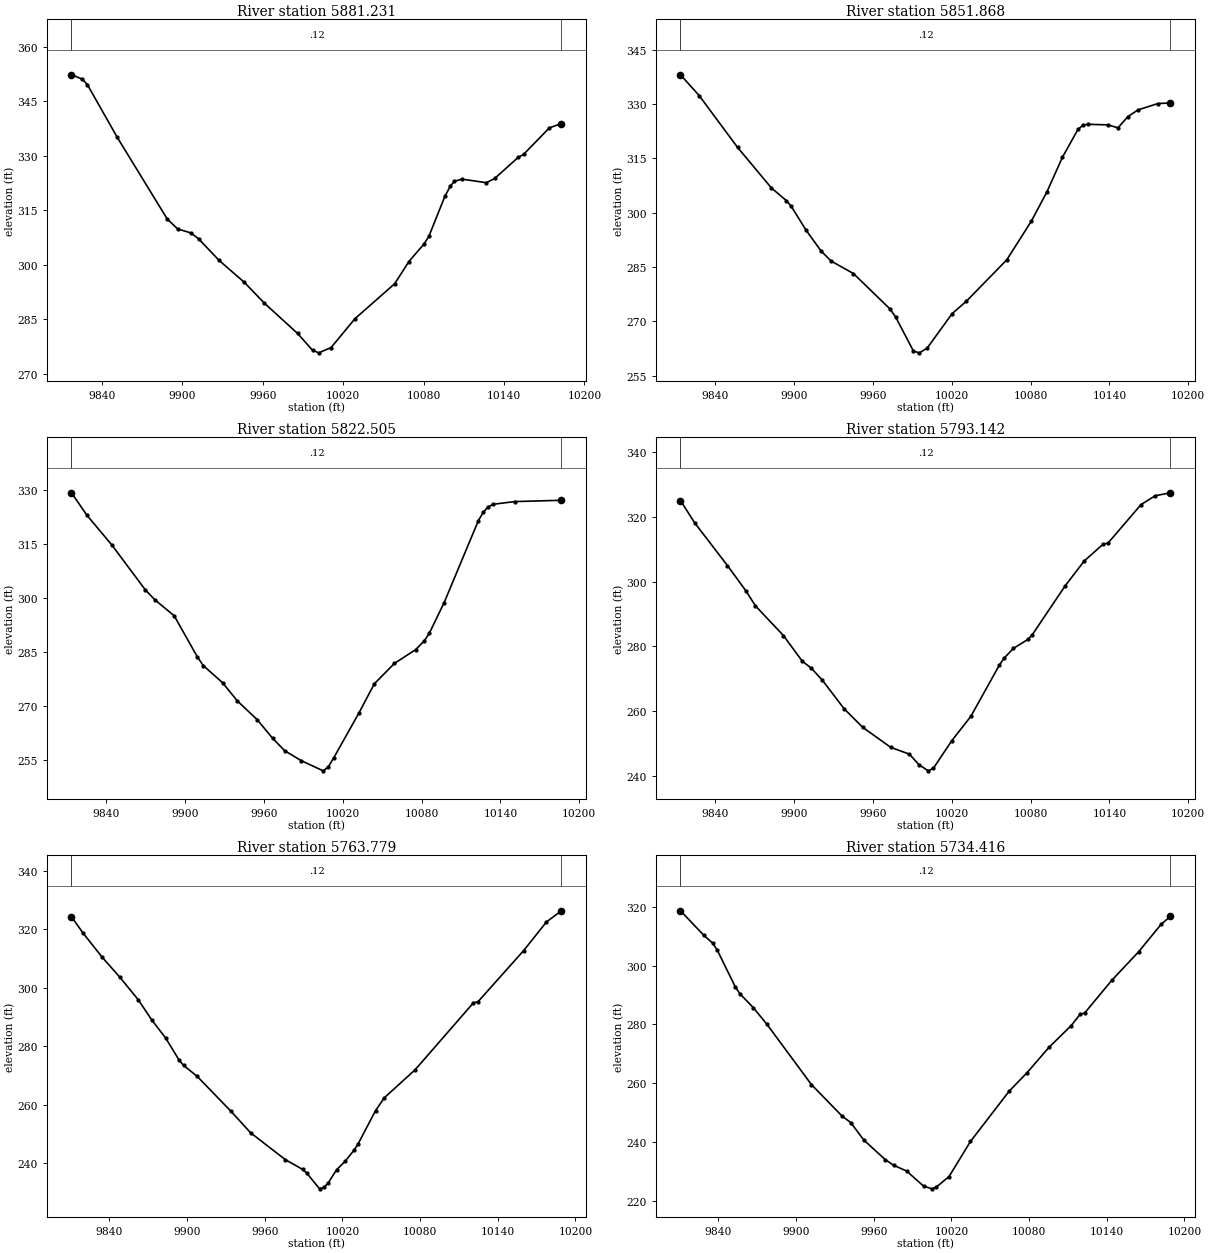
Type RM Length L Ch R = 1 ,5881.231,29.362900,29.362900,29.362900
XS GIS Cut Line= 6
1189530.00705251835465.3887471131189498.85671116835406.880326218
1189475.43378107835369.8476588071189451.74318721835339.777953866
1189383.55418791835266.2510993841189319.45432823835168.405143286
#Sta/Elev= 30
9817.131352.31959825.255351.12229828.972349.62899851.273335.10929888.665312.5876
9896.429309.87439906.058308.81659911.957307.19619927.234301.24989946.053295.2277
9960.918289.52759985.897281.12569997.075276.4844 10001.7275.779210010.92277.2254
10028.68285.157110058.46294.824310068.95300.896710080.28305.730510083.92307.8436
10095.99318.961410100.02321.699510102.95323.002710108.61323.596210126.85322.6119
10133.08323.784910150.72329.620610154.58330.385310173.88337.712810182.89338.8909
#Mann= 3 , 0 , 0
9817.131    0.12       09817.131    0.12       010182.89    0.12       0
#XS Ineff= 2 , 0
       0                               0
Bank Sta=9817.131,10182.89
Exp/Cntr=0.3,0.1

Type RM Length L Ch R = 1 ,5851.868,29.363000,29.363000,29.363000
XS GIS Cut Line= 6
1189546.68739023835451.2401761571189515.66237878835388.664561486
1189490.27881961835345.1912061991189467.89532307 835315.02304697
1189405.80009991835244.3966700351189342.00930597835141.652982872
#Sta/Elev= 30
9813.579338.10129827.763332.37329857.059 318.0139882.692306.85859894.062303.3449
9897.862301.73899909.259295.09229920.657289.36389928.255286.61879945.189 283.176
9972.922273.42399977.344271.13299990.894261.73119995.387261.265210001.26262.5596
10020.33272.117510031.21275.5573 10061.9286.977910080.58297.662310092.43305.7335
10104.28315.356310116.03322.986310119.84324.195710123.64324.417610138.88324.2588
 10146.5323.445610154.11326.561510161.73328.392710176.96330.160210186.44 330.309
#Mann= 3 , 0 , 0
9813.579    0.12       09813.579    0.12       010186.44    0.12       0
#XS Ineff= 2 , 0
       0                               0
Bank Sta=9813.579,10186.44
Exp/Cntr=0.3,0.1

Type RM Length L Ch R = 1 ,5822.505,29.362900,29.362900,29.362900
XS GIS Cut Line= 6
1189557.26757432835440.4594880291189527.99852047835377.038456482
1189502.45997996835326.8814791381189470.27649877835274.687837329
1189433.31060937835215.7676664161189377.87597505835113.983218789
#Sta/Elev= 30
9813.548329.28289825.236323.06739844.577314.62819869.871 302.2349877.097299.5039
9891.705295.10129909.222283.73639913.795281.25569928.521276.48489939.681 271.453
9954.982266.16639966.548261.05459975.834257.56169988.328254.829310005.11251.9732
10008.98253.045910013.21255.634510032.22267.986210044.08276.187810059.33 281.835
10075.43285.656810082.14288.146610085.88290.213810097.09298.669410123.24321.5469
10126.97323.852710130.31325.267610134.44326.085110150.89326.835510186.46327.1953
#Mann= 3 , 0 , 0
9813.548    0.12       09813.548    0.12       010186.46    0.12       0
#XS Ineff= 2 , 0
       0                               0
Bank Sta=9813.548,10186.46
Exp/Cntr=0.3,0.1

Type RM Length L Ch R = 1 ,5793.142,29.363000,29.363000,29.363000
XS GIS Cut Line= 5
1189567.40918869 835432.172897481189501.84323671835273.956867677
1189496.03663736835260.9943962871189495.37366537835259.107476008
1189419.17805687835090.014449412
#Sta/Elev= 30
9813.533 324.9679824.406318.05599849.265304.94259863.471297.04389870.574292.5138
9891.882283.35799906.088275.51689913.191 273.2539921.376269.6556 9938.05260.7985
9952.256255.05169973.564248.89269987.806246.78069994.996243.552210002.12241.6479
10006.01242.442110020.11250.980110034.51258.4306 10056.1274.1397 10059.7276.3259
10066.89279.372210077.88282.143710081.29 283.59810106.48298.772310120.87 306.355
10135.27311.542910138.86311.822210164.05 323.71810174.85326.445710186.47327.3663
#Mann= 3 , 0 , 0
9813.533    0.12       09813.533    0.12       010186.47    0.12       0
#XS Ineff= 2 , 0
       0                               0
Bank Sta=9813.533,10186.47
Exp/Cntr=0.3,0.1

Type RM Length L Ch R = 1 ,5763.779,29.362900,29.362900,29.362900
XS GIS Cut Line= 6
 1189579.2384421835433.966355242 1189535.7002942835318.917887696
1189526.67600039835282.4532238831189522.46665952835232.203098919
1189514.67231565835195.153210723 1189470.2499067835073.457690242
#Sta/Elev= 30
 9810.75324.20769819.961318.50589834.086310.59169848.211303.50549862.337  295.84
9872.931288.82829883.523282.75889893.953275.14529897.429273.37149907.858269.6443
9933.787257.78299949.136250.33529976.054241.12849989.236237.84459992.531236.5416
10002.41231.1708 10005.7231.651410008.99233.121210015.57237.695210022.16240.5973
10028.86244.294610032.21246.566110045.62 257.89710052.33262.277910076.26271.9198
10121.27294.8034 10124.8295.170110160.07312.6619 10177.7322.476910189.26326.2771
#Mann= 3 , 0 , 0
 9810.75    0.12       0 9810.75    0.12       010189.26    0.12       0
#XS Ineff= 2 , 0
       0                               0
Bank Sta=9810.75,10189.26
Exp/Cntr=0.3,0.1

Type RM Length L Ch R = 1 ,5734.416,29.363000,29.363000,29.363000
XS GIS Cut Line= 6
1189599.76317289835435.6872055491189562.47385387835325.355876699
1189555.33943509835287.7518204641189552.28871231835229.483937444
1189546.67566942835194.0970177791189506.57985925835070.988804776
#Sta/Elev= 30
9810.741318.6284 9828.65 310.3459835.628307.61149839.117305.28659853.074292.7537
9856.563290.4682 9867.03285.65689877.498280.05169911.851259.56669935.608248.8156
9942.287246.62529952.305240.70889968.946234.02489975.518232.07849985.377230.1666
9998.521225.023410005.09224.095610008.37224.696110018.23228.288110034.77240.2165
10064.79257.374210078.41263.550110095.43272.213210112.49279.554310119.46283.4334
10122.94283.852510143.85294.943310164.77304.740610182.19314.101810189.26316.7099
#Mann= 3 , 0 , 0
9810.741    0.12       09810.741    0.12       010189.26    0.12       0
#XS Ineff= 2 , 0
       0                               0
Bank Sta=9810.741,10189.26
Exp/Cntr=0.3,0.1

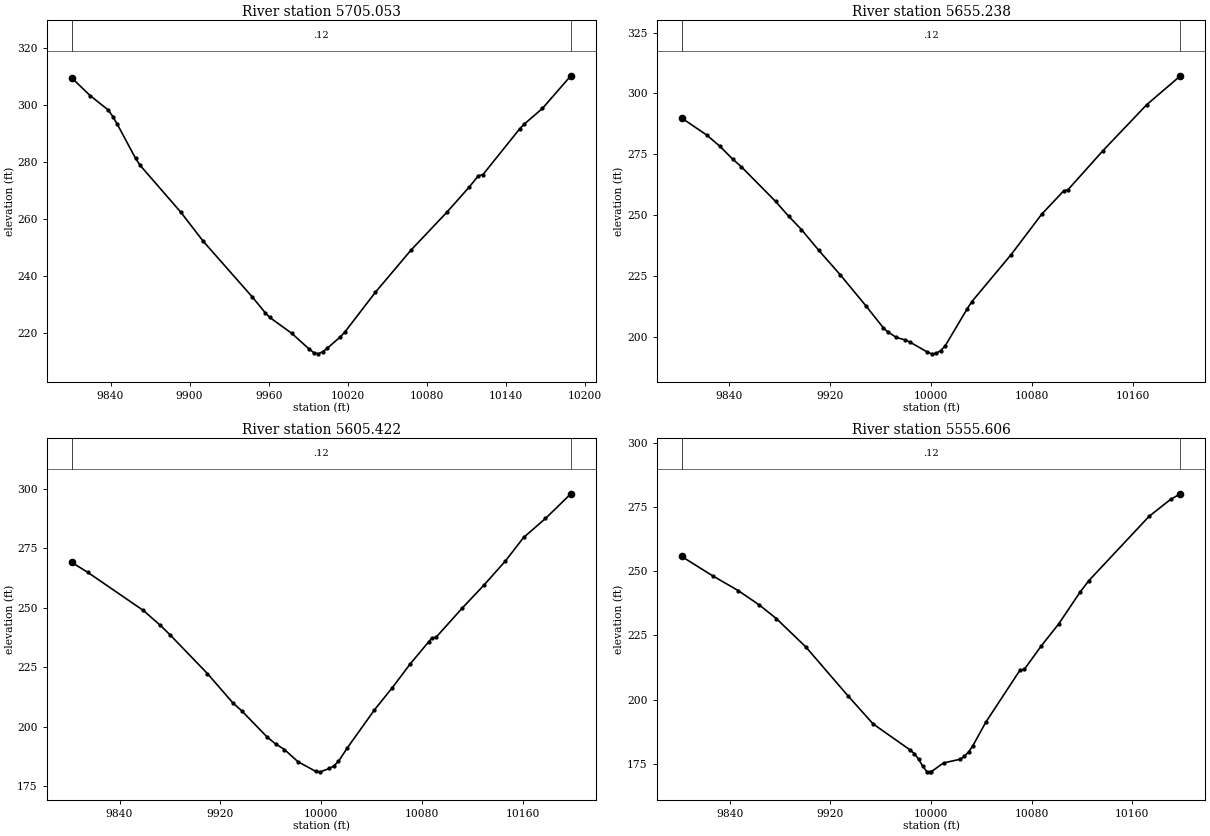
Type RM Length L Ch R = 1 ,5705.053,49.815800,49.815800,49.815800
XS GIS Cut Line= 6
1189630.78973325835435.2248357621189610.94125594835374.912939573
1189596.33209436835322.5587387021189576.80204652835218.465249651
1189567.04511595  835177.33510031189531.91864856835070.446999129
#Sta/Elev= 30
9810.719309.29249824.507303.15719838.322298.08639841.776295.7882 9845.23293.0237
9859.046281.0984  9862.5278.66179893.317262.25389910.348252.0408 9947.45232.5686
9957.474226.91849960.816225.31659977.523219.73639990.889214.1507 9994.23212.9584
9997.571212.538810000.94213.266310004.27214.427410014.25218.430710017.58220.0396
10040.97 234.13410067.95248.907110095.22262.228510112.36 271.15210119.21275.0592
10122.64275.442710150.38291.436510153.86 293.10910167.76298.6644 10189.3310.1023
#Mann= 3 , 0 , 0
9810.719    0.12       09810.719    0.12       0 10189.3    0.12       0
#XS Ineff= 2 , 0
       0                               0
Bank Sta=9810.719,10189.3
Exp/Cntr=0.3,0.1

Type RM Length L Ch R = 1 ,5655.238,49.815700,49.815700,49.815700
XS GIS Cut Line= 6
1189686.46541228835424.9466325221189642.50325386835271.167901626
1189629.80769729835236.5989810061189628.92796239835234.802855589
1189615.73009902835200.665308429 1189564.1993979835049.004173842
#Sta/Elev= 30
9802.234289.91499822.227282.87569832.464278.3612  9842.7273.04149849.525269.9135
9876.823255.5984 9887.06249.58079897.297244.04119910.946235.55379928.007225.4877
9948.481212.64259962.174203.69529965.624202.05399972.614199.68779979.604198.6827
9983.099197.8637 9997.08193.705410000.65192.969610004.18193.182210007.69194.3107
10011.21196.2136 10028.8  211.5710032.32  214.3910063.58233.791810087.84250.4023
10105.16259.914810108.63260.427310136.35276.4836   10171295.344210197.78307.2449
#Mann= 3 , 0 , 0
9802.234    0.12       09802.234    0.12       010197.78    0.12       0
#XS Ineff= 2 , 0
       0                               0
Bank Sta=9802.234,10197.78
Exp/Cntr=0.3,0.1

Type RM Length L Ch R = 1 ,5605.422,49.815800,49.815800,49.815800
XS GIS Cut Line= 6
1189729.20335859835408.0282501211189687.69814476835246.968034203
1189676.03358671835218.8821359881189675.09781126835217.114560155
1189654.03108276835167.8297180461189607.78038527835032.355877113
#Sta/Elev= 30
9802.266269.11969814.809264.97849858.854248.96039872.406242.68269879.821 238.844
9909.674222.42979930.002210.01429936.778206.83079957.106195.69659963.882192.8082
9970.759190.49659981.417185.39569995.627181.2952    9999181.130510006.39182.5576
10009.96183.676710013.53185.519310020.67191.277710042.07207.1662 10056.3216.5499
10070.16226.307210084.92235.7146 10087.5237.287510090.96237.716210111.76250.0123
 10129.1259.743810145.85269.7377 10160.3279.633710177.63 287.60910197.75 297.998
#Mann= 3 , 0 , 0
9802.266    0.12       09802.266    0.12       010197.75    0.12       0
#XS Ineff= 2 , 0
       0                               0
Bank Sta=9802.266,10197.75
Exp/Cntr=0.3,0.1

Type RM Length L Ch R = 1 ,5555.606,49.815800,49.815800,49.815800
XS GIS Cut Line= 6
1189755.45867741835400.3120894151189722.83712539835250.536418634
1189720.45967558835225.4142976721189723.75604981835195.936716276
 1189722.0538221835179.8013262561189673.53821197835014.383297358
#Sta/Elev= 30
9801.582255.72439826.368248.14989846.601 242.4429863.462236.8104 9876.95231.5437
9900.446220.48979933.853201.52989953.898190.56899983.571180.34879986.867178.9183
9990.163176.81739993.459174.04869996.755171.9284    9999171.900110000.07171.9137
   10010175.362810023.19176.799910026.51 177.94210029.91179.636310033.32182.0621
10043.54191.1797 10070.8211.467910074.21211.756910087.84220.977710101.47229.3746
10118.55241.796410125.42246.217810173.45271.287110190.61277.907110198.43280.0779
#Mann= 3 , 0 , 0
9801.582    0.12       09801.582    0.12       010198.43    0.12       0
#XS Ineff= 2 , 0
       0                               0
Bank Sta=9801.582,10198.43
Exp/Cntr=0.3,0.1