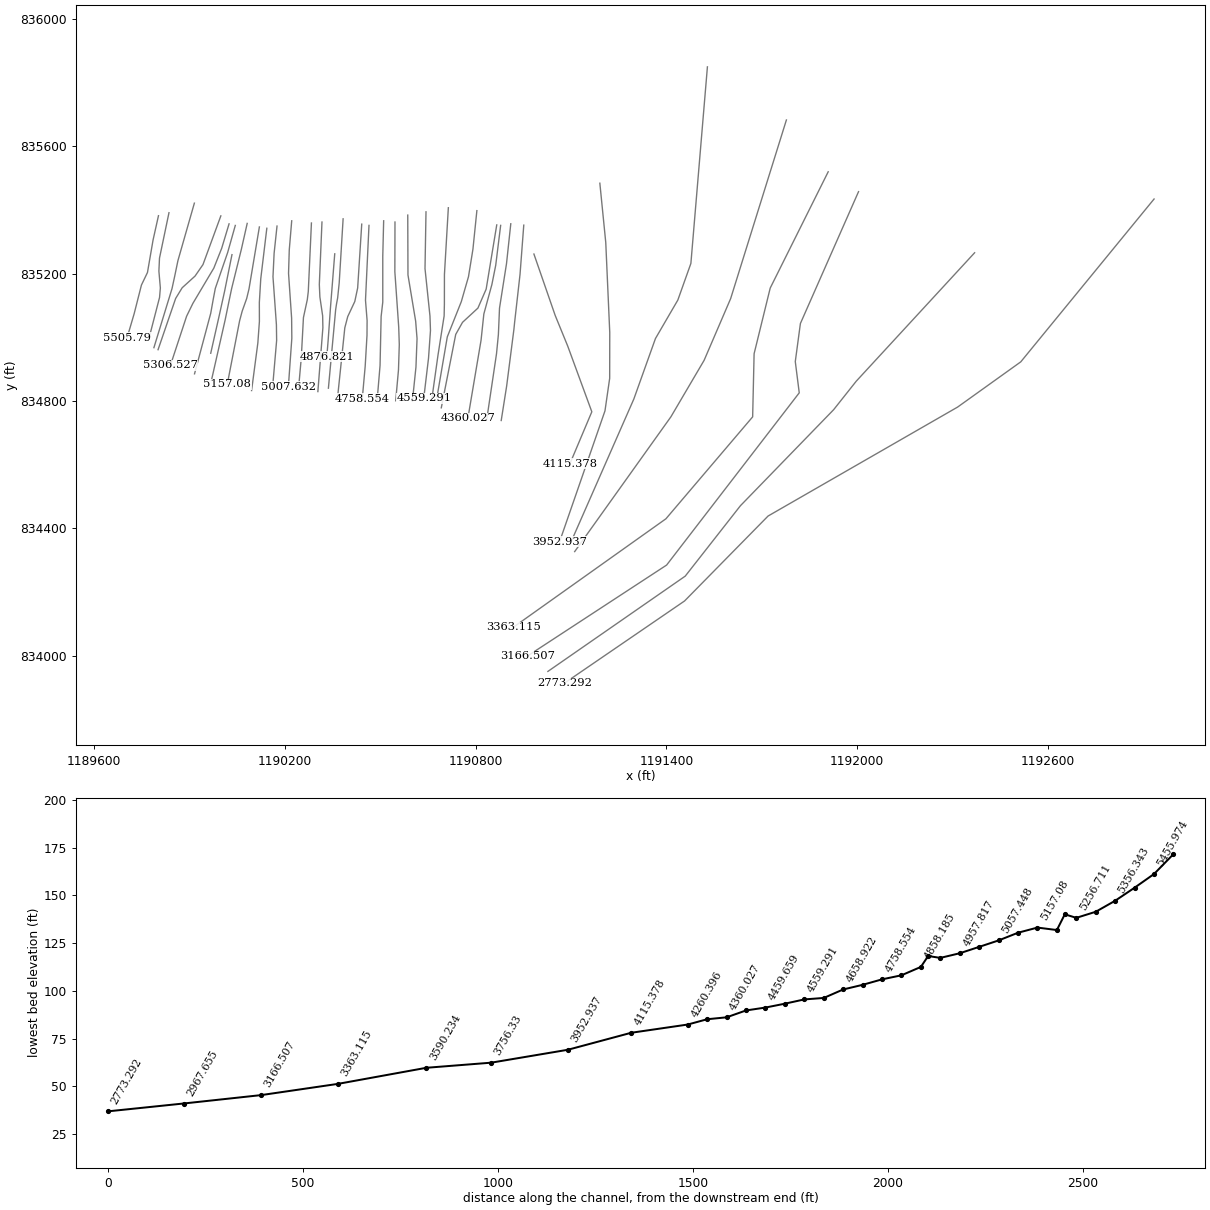
HEC-RAS study 79_ras.prj: 79

--- 79_ras.g01 (geometry) --- (continued)

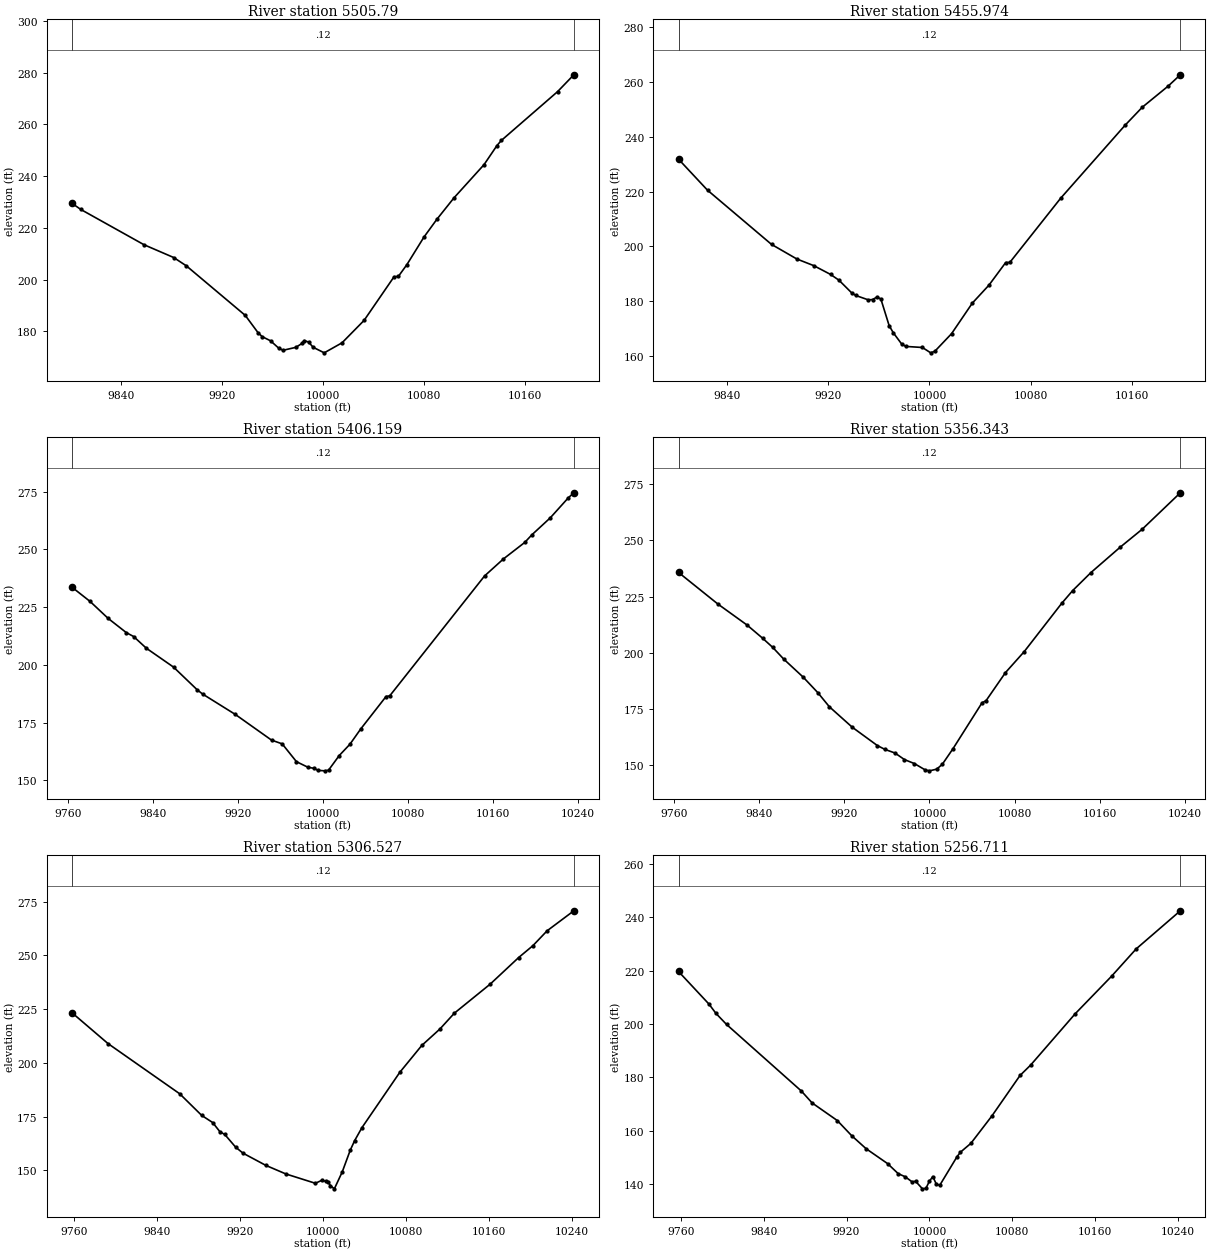
Type RM Length L Ch R = 1 , 5505.79,49.815800,49.815800,49.815800
XS GIS Cut Line= 6
1189803.20952248835382.5222313331189786.20174438835306.185470313
1189768.60360668835204.0600794941189749.63344605835164.595141139
1189726.73540403835074.4556454421189704.68489381834999.631987748
#Sta/Elev= 30
9801.561229.46429808.443227.11549858.461213.46469881.969208.50959891.956205.2977
9938.565186.12619948.552179.51179951.882177.9255 9958.54176.30779965.198173.3749
9968.527172.64749978.515173.7681  9983.4 175.2839985.245 176.3989988.708175.7944
9992.172173.8178   10001171.649910015.09175.528510032.53184.196710056.23201.0789
10059.61 201.19110066.38205.759810079.92216.451410090.08223.287410103.62231.5857
10127.39244.428510137.65251.838510141.07253.786210185.53272.660910198.45279.1979
#Mann= 3 , 0 , 0
9801.561    0.12       09801.561    0.12       010198.45    0.12       0
#XS Ineff= 2 , 0
       0                               0
Bank Sta=9801.561,10198.45
Exp/Cntr=0.3,0.1

Type RM Length L Ch R = 1 ,5455.974,49.815700,49.815700,49.815700
XS GIS Cut Line= 6
 1189836.2199945 835391.929370951189806.43322941835249.275015738
 1189804.5371136835208.3684711921189809.12071707835155.514312319
1189806.60979668835125.6503280851189774.77918244835002.736258547
#Sta/Elev= 30
9801.579231.79249824.504220.49039875.109200.7497 9895.17195.42079908.486193.0144
9921.801189.80739928.459187.69589938.446183.11289941.775182.12819951.703180.5304
9954.987180.66179958.271181.49669961.556 180.9019968.124171.15539971.409168.5512
9977.977164.48499981.262163.57559994.412163.189310001.02161.236810004.31161.8318
10017.48168.211610033.94179.367210047.11185.926910060.28194.127310063.57194.1803
 10103.7217.530310154.62244.114110168.27250.700310188.74258.4042 10198.4262.5446
#Mann= 3 , 0 , 0
9801.579    0.12       09801.579    0.12       0 10198.4    0.12       0
#XS Ineff= 2 , 0
       0                               0
Bank Sta=9801.579,10198.4
Exp/Cntr=0.3,0.1

Type RM Length L Ch R = 1 ,5406.159,49.815800,49.815800,49.815800
XS GIS Cut Line= 6
1189916.07002998835422.0110861651189864.33735948835241.191148612
 1189854.8159908835195.2818016731189854.40923826835193.323600364
1189845.84553093835153.7595336651189788.85091454834967.821782615
#Sta/Elev= 30
9764.039 233.5969780.979 227.4579798.042 220.0819815.104213.93589821.929212.2631
9833.888207.18899859.466199.00639881.598189.23549886.766187.35439917.478178.5318
9951.603167.38549961.664165.75029975.066158.03859985.846155.6212 9991.82155.1328
 9995.17 154.27610001.87154.066810005.23154.3468 10015.3 160.69610025.37165.5955
10035.44172.167110059.33186.273710062.76186.533510151.98238.501510169.68245.8606
10189.72253.008110196.59256.373210213.75263.6671 10230.9272.429710235.96274.5356
#Mann= 3 , 0 , 0
9764.039    0.12       09764.039    0.12       010235.96    0.12       0
#XS Ineff= 2 , 0
       0                               0
Bank Sta=9764.039,10235.96
Exp/Cntr=0.3,0.1

Type RM Length L Ch R = 1 ,5356.343,49.815800,49.815800,49.815800
XS GIS Cut Line= 6
 1189999.2874554835381.9657833181189943.13754457835228.921288693
1189918.18162359835192.7793989561189877.73015887835156.072036622
1189857.20179503835122.500408042 1189801.9010975834961.472262209
#Sta/Elev= 30
9764.092235.73089801.094221.64159828.608212.23879843.046  206.439852.683202.2913
9863.099197.03599881.493188.94299894.936182.17249905.895175.82589927.411 166.698
9950.994158.52879958.057156.81559967.633 155.1859976.514152.25559985.858150.4799
9996.173147.601110000.05147.236710006.86147.9885 10012.1150.159610022.18157.1235
10049.48177.5992 10053.2178.498810071.46191.040910089.06200.379710124.28 221.897
10134.69227.6467 10151.9235.695510179.43247.029810200.08 255.01510235.91271.2698
#Mann= 3 , 0 , 0
9764.092    0.12       09764.092    0.12       010235.91    0.12       0
#XS Ineff= 2 , 0
       0                               0
Bank Sta=9764.092,10235.91
Exp/Cntr=0.3,0.1

Type RM Length L Ch R = 1 ,5306.527,49.815800,49.815800,49.815800
XS GIS Cut Line= 6
1190025.14156365835356.9054796491190001.96481668835280.081624193
1189977.23344969835217.7978504671189911.36065232835106.946149002
1189891.56201209 835066.389921971189840.66586263834911.898896684
#Sta/Elev= 30
9757.935223.32939792.616209.02649861.845185.65519883.025175.60629893.615172.2854
9900.675167.96789905.193166.79369915.759160.84419922.809158.06919944.929 152.361
9964.252148.38149992.722144.04039998.704 145.38810003.34144.942710005.17144.5902
10007.17142.9487   10011141.458510018.67149.397410026.33159.418410030.57163.8714
10037.65169.939810074.16195.656810095.36208.150410112.84215.794510126.82223.1751
10161.37236.676810188.83249.046510202.56 254.55410216.29 261.486 10242.1270.7949
#Mann= 3 , 0 , 0
9757.935    0.12       09757.935    0.12       0 10242.1    0.12       0
#XS Ineff= 2 , 0
       0                               0
Bank Sta=9757.935,10242.1
Exp/Cntr=0.3,0.1

Type RM Length L Ch R = 1 ,5256.711,29.497300,29.497300,29.497300
XS GIS Cut Line= 6
1190044.74025872835351.9224402081190020.79691015 835267.05691476
1189981.90535633835154.1263699691189975.64965616835121.263717808
1189967.47041946835075.7454933851189916.57178719 834885.58452944
#Sta/Elev= 30
9757.929219.6525 9787.25207.47099794.068203.95419804.294199.81289876.414174.9137
9886.824170.44469911.114163.85529924.994 158.1829938.873153.32739959.693147.7152
9969.932143.95389976.611142.81719983.291140.89249986.631141.1224 9993.31138.2832
 9996.65138.47179999.977141.1447 10003.3142.871310006.64140.078510009.97139.6067
10026.65150.314810029.98152.020510039.99155.302710060.27165.557610087.44180.7276
10097.63184.595910140.71203.847810175.75217.879410199.52228.117910242.11242.3838
#Mann= 3 , 0 , 0
9757.929    0.12       09757.929    0.12       010242.11    0.12       0
#XS Ineff= 2 , 0
       0                               0
Bank Sta=9757.929,10242.11
Exp/Cntr=0.3,0.1

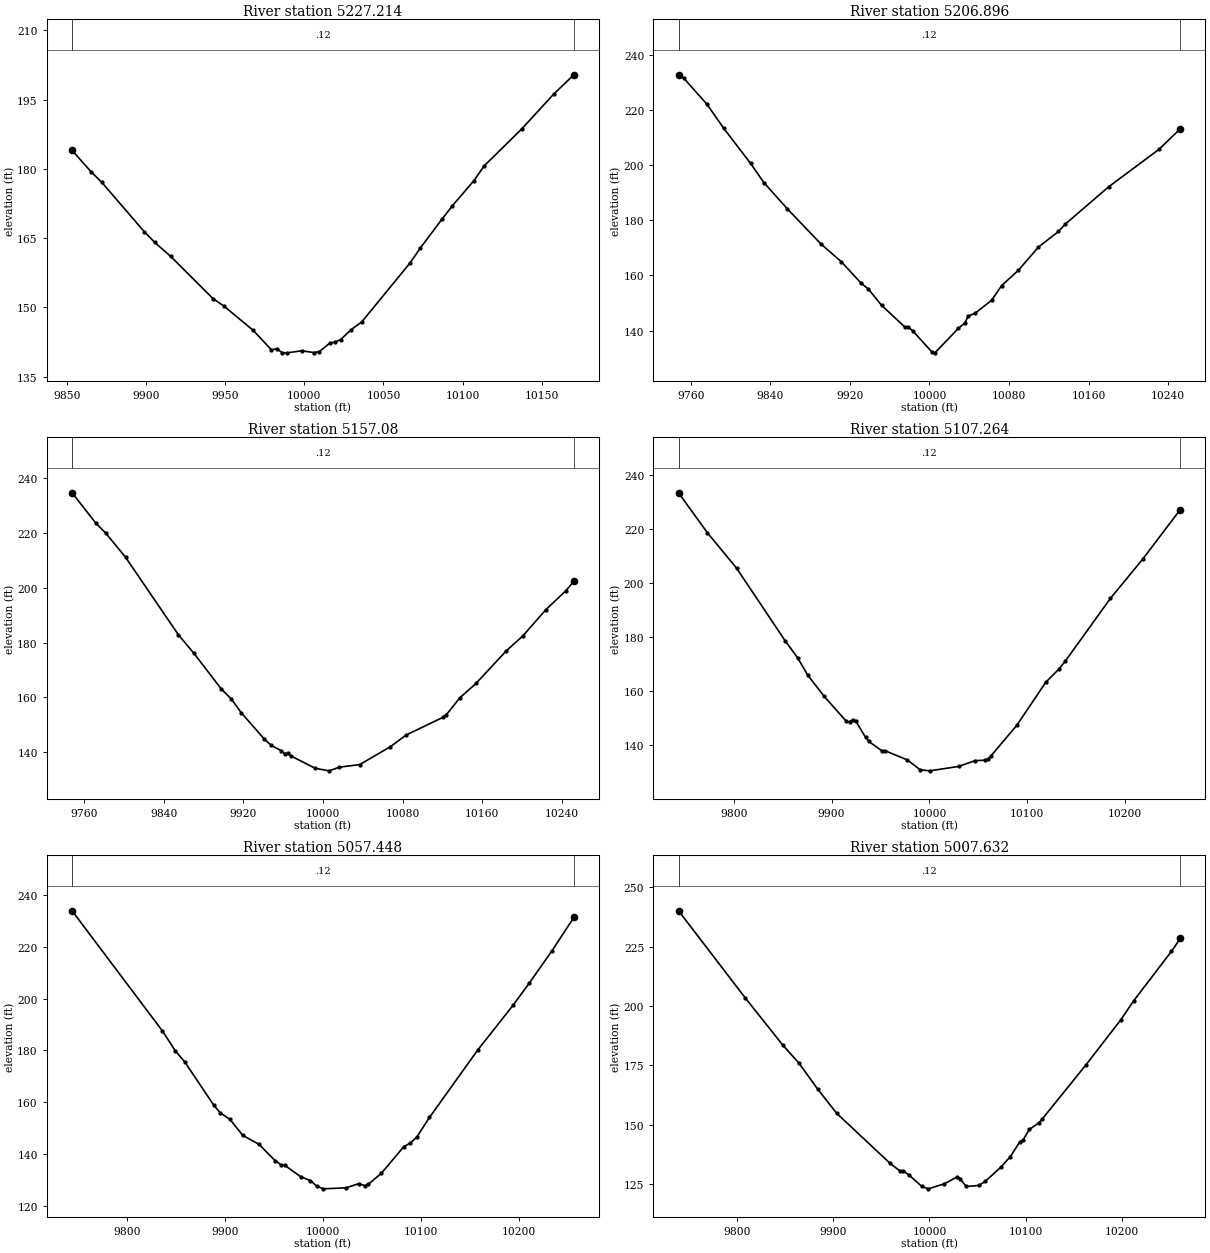
Type RM Length L Ch R = 1 ,5227.214,20.318400,20.318400,20.318400
XS GIS Cut Line= 4
1190034.28144306835260.103911161 1190011.1383535 835145.27858223
1189994.22609577835068.7283629631189967.52253091834950.342558742
#Sta/Elev= 30
9853.367183.97829865.465179.32249872.158 177.0589898.933166.38159905.626164.0377
9915.667161.00929942.441151.85499949.135150.30089967.727145.01429979.291140.7765
9982.651141.0129 9986.01140.1706 9989.37140.13519998.377140.585810006.17140.1913
10009.53140.404210016.25142.276610019.61 142.46510022.97143.016510029.69145.1769
10036.41146.871810066.67159.540210073.39162.877410086.85169.023510093.57171.9953
10107.03177.382310113.75180.6725 10137.3188.610510157.47196.148110170.26200.3549
#Mann= 3 , 0 , 0
9853.367    0.12       09853.367    0.12       010170.26    0.12       0
#XS Ineff= 2 , 0
       0                               0
Bank Sta=9853.367,10170.26
Exp/Cntr=0.3,0.1

Type RM Length L Ch R = 1 ,5206.896,49.815800,49.815800,49.815800
XS GIS Cut Line= 6
1190082.14690002835358.2863755491190064.10692587835278.226544498
1190033.17942257 835153.236021191190024.90841031835113.564354929
1190012.67463704 835054.299155391189969.98859305834866.241847681
#Sta/Elev= 30
9747.648  232.93 9752.83231.72499776.372222.14789793.188213.44029820.092200.7334
9833.564193.73419857.222 184.165 9891.02 171.3989911.299165.03179931.577157.0921
9938.337 155.1749951.856149.16719975.371141.24759978.723141.24119983.409139.8219
10002.18 132.30910005.53131.891510028.98140.745210035.68142.757210039.03145.3069
10045.73146.222810062.49150.963310072.59156.308210089.41161.861910109.59170.2945
10129.78175.988710136.51178.619810180.24192.213310230.71205.779110252.36213.2992
#Mann= 3 , 0 , 0
9747.648    0.12       09747.648    0.12       010252.36    0.12       0
#XS Ineff= 2 , 0
       0                               0
Bank Sta=9747.648,10252.36
Exp/Cntr=0.3,0.1

Type RM Length L Ch R = 1 , 5157.08,49.815800,49.815800,49.815800
XS GIS Cut Line= 6
 1190120.4641236835347.1816383261190087.85049836835152.482882842
 1190080.5549373835122.2974196421190066.44413761835082.688187072
1190058.31541362835052.2893524661190019.60751056834853.332303159
#Sta/Elev= 30
9747.667234.75499771.473223.70749781.452220.06439801.412211.22579854.636182.8652
 9869.91176.25649897.881163.01959907.861159.41719917.841154.41159941.126144.7405
9947.819142.50829957.945140.5766 9961.32139.47099964.696139.57479968.071138.5771
9992.158 134.12410006.11 133.18610016.57 134.53810036.99135.469410067.27141.8862
10083.99146.335510120.75152.731210124.09153.683410137.46159.787910154.17   165.2
10184.26176.983110200.97182.448310224.36192.115110244.42199.016610252.34202.4351
#Mann= 3 , 0 , 0
9747.667    0.12       09747.667    0.12       010252.34    0.12       0
#XS Ineff= 2 , 0
       0                               0
Bank Sta=9747.667,10252.34
Exp/Cntr=0.3,0.1

Type RM Length L Ch R = 1 ,5107.264,49.815700,49.815700,49.815700
XS GIS Cut Line= 6
1190143.87812703835343.0335505781190124.81991393835184.340798299
1190120.35693131835109.7173719041190120.54439381835050.367835888
1190115.66644448834982.7318817861190095.94518587834833.043832391
#Sta/Elev= 30
9743.601233.29679773.045218.54029802.846205.44589852.424 178.6459865.614172.0956
9875.506165.92859891.992158.20329915.036148.81049918.323   148.69921.609149.4266
9924.896148.77969934.756142.85269938.043141.3496 9951.19137.92779954.476137.9399
9977.483134.50319990.608130.845110000.46130.479910029.99132.122510046.41134.2337
10056.28134.409610059.57134.757110062.86135.990610089.18147.260910118.83163.2055
10132.05168.004410138.65170.949910184.89194.223910218.06208.808710256.39227.1066
#Mann= 3 , 0 , 0
9743.601    0.12       09743.601    0.12       010256.39    0.12       0
#XS Ineff= 2 , 0
       0                               0
Bank Sta=9743.601,10256.39
Exp/Cntr=0.3,0.1

Type RM Length L Ch R = 1 ,5057.448,49.815800,49.815800,49.815800
XS GIS Cut Line= 6
1190175.91674187835349.9643314421190166.78820918835264.319655805
1190163.22375849835190.6941158531190174.02554032835039.904829205
 1190174.7087093834990.5336556271190161.62039294834838.830570141
#Sta/Elev= 30
9743.624234.02619835.994 187.5229849.133179.85499858.987175.43059888.549158.7421
9895.119155.83239904.971153.3353  9918.1147.10739934.511143.71719950.968137.4085
9957.559135.65499960.854135.59259977.331131.12869987.217129.63719993.808127.4336
10000.39 126.45410023.43126.846710036.59128.453110043.17127.646710046.46128.2518
10059.61132.430710082.58142.754510089.14144.1519 10095.7146.378310108.83154.0845
10158.13180.148110194.35197.517610210.86206.057210233.97218.523610256.38231.4435
#Mann= 3 , 0 , 0
9743.624    0.12       09743.624    0.12       010256.38    0.12       0
#XS Ineff= 2 , 0
       0                               0
Bank Sta=9743.624,10256.38
Exp/Cntr=0.3,0.1

Type RM Length L Ch R = 1 ,5007.632,49.815800,49.815800,49.815800
XS GIS Cut Line= 6
1190222.11332903835366.4577201191190214.41317467835274.572155502
1190212.14200554835201.4746960831190221.82753383835060.763278004
1190222.47897101 834997.185353291190211.62303389834845.401410962
#Sta/Elev= 30
9738.878 240.0779808.121203.51759847.579183.45599863.991176.07129883.685165.0533
 9903.38154.89739959.186133.7533 9969.07130.67479972.364130.72589978.953128.8463
 9992.13124.06179998.719123.076110015.19125.142710028.37127.958710031.67127.4153
10038.26124.072110051.41124.483810057.97126.193710074.38132.189710084.22136.6465
10094.06142.845510097.35143.555610103.91 148.05310113.76150.794910117.04152.2845
10163.02175.310110199.21194.203410212.39202.103510251.93223.037610261.12228.4693
#Mann= 3 , 0 , 0
9738.878    0.12       09738.878    0.12       010261.12    0.12       0
#XS Ineff= 2 , 0
       0                               0
Bank Sta=9738.878,10261.12
Exp/Cntr=0.3,0.1

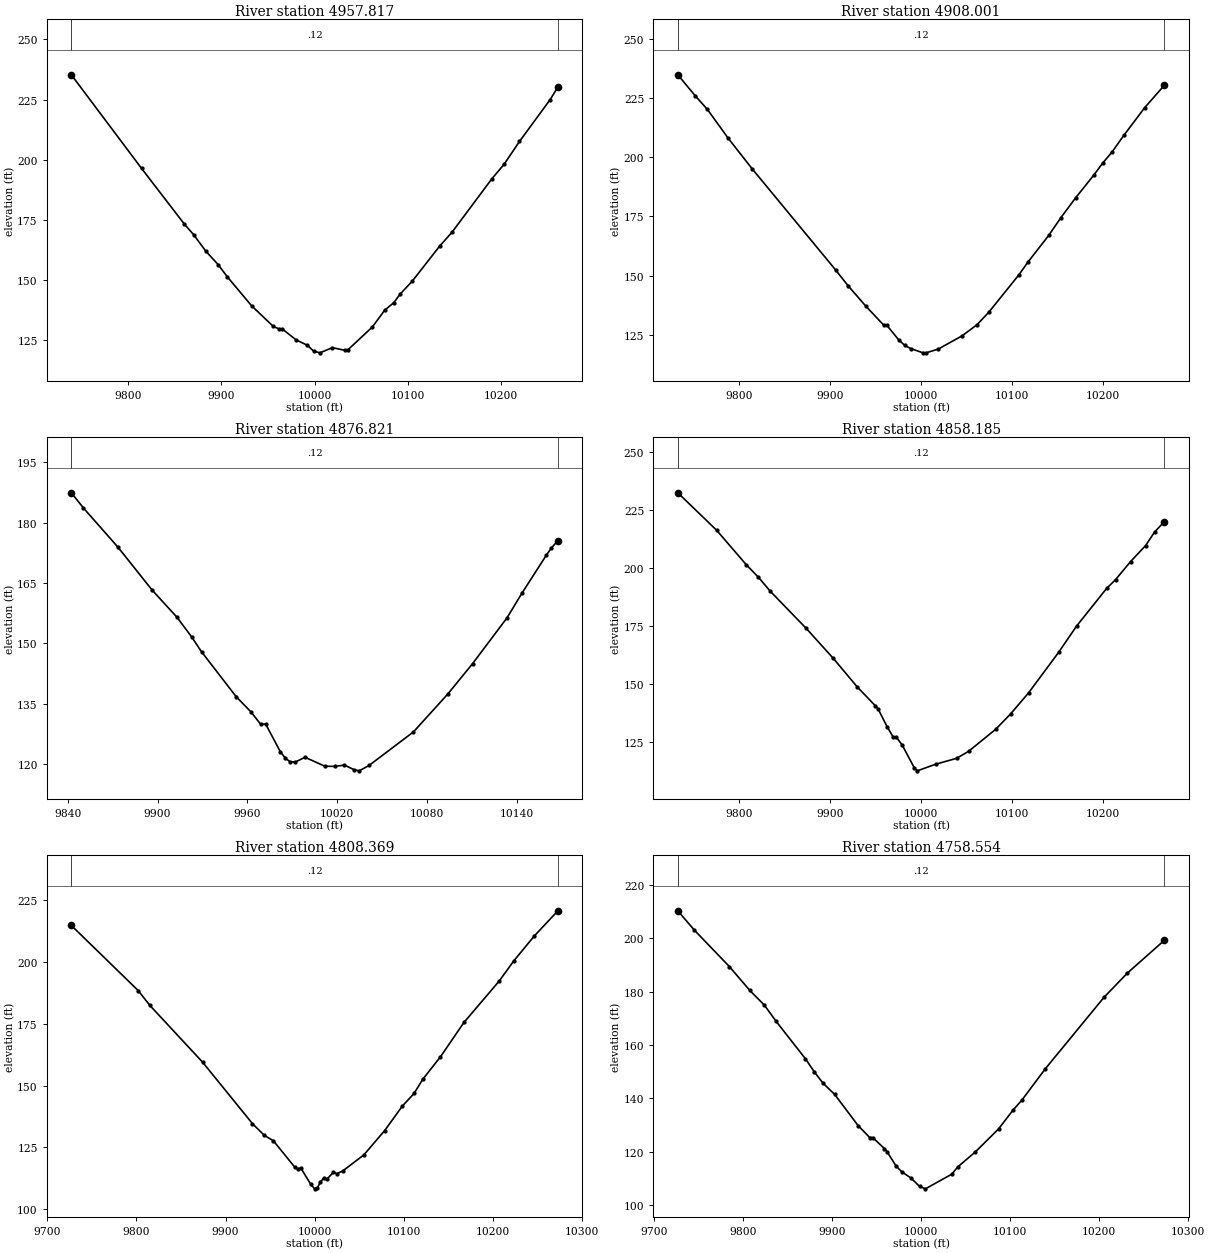
Type RM Length L Ch R = 1 ,4957.817,49.815800,49.815800,49.815800
XS GIS Cut Line= 6
1190284.11075649835359.590219161 1190274.2396128835144.270460463
1190271.15942392835118.7953742381190259.00575605 835062.43683052
 1190252.1577147834935.0036518391190243.63070234834839.705828023
#Sta/Elev= 30
9738.878235.3083 9814.28196.3872 9860.26173.22189870.108168.87089883.239161.9957
 9896.37156.44979906.218151.3771 9932.48139.25339955.465130.78599962.075129.6106
9965.379129.63029980.105125.12739992.076122.90859998.831120.505410005.64119.7339
10019.12121.8964 10032.4120.780510035.72120.989110062.03130.498210075.17137.4324
10085.03140.5982 10091.6144.063310104.74149.499910134.31164.132210147.45169.8489
10190.23192.0666 10203.4198.120110219.87207.580710252.81224.991210261.12230.2021
#Mann= 3 , 0 , 0
9738.878    0.12       09738.878    0.12       010261.12    0.12       0
#XS Ineff= 2 , 0
       0                               0
Bank Sta=9738.878,10261.12
Exp/Cntr=0.3,0.1

Type RM Length L Ch R = 1 ,4908.001,31.179500,31.179500,31.179500
XS GIS Cut Line= 6
1190317.26721424835362.6574702381190308.94521808835166.524644796
1190310.70345929835127.1510759381190319.38217968835067.842155432
1190320.11587594835030.5080240251190304.37407421834829.810904208
#Sta/Elev= 30
9732.813234.88269752.114225.9127 9765.26220.27149788.264207.99379814.554195.0841
9906.478152.19999919.605 145.7659939.303137.05079959.008129.01039962.292128.9991
9975.506122.75159982.148120.43089988.791119.083610002.06117.322110005.37117.3086
10018.62118.862110044.96124.486310061.37129.182310074.51134.556310107.38150.3021
10117.24155.626410140.26167.0209 10153.4174.412410169.85182.939810189.62192.4309
 10199.5197.589510209.39202.051210222.57209.228710245.64221.019510267.18230.4737
#Mann= 3 , 0 , 0
9732.813    0.12       09732.813    0.12       010267.18    0.12       0
#XS Ineff= 2 , 0
       0                               0
Bank Sta=9732.813,10267.18
Exp/Cntr=0.3,0.1

Type RM Length L Ch R = 1 ,4876.821,18.636200,18.636200,18.636200
XS GIS Cut Line= 4
1190357.39457795835262.7742676591190344.04279551835094.541808993
1190336.92184484 834993.958381341190332.47125074834938.771013945
#Sta/Elev= 30
 9842.38187.45229850.373183.71769873.411173.97939896.449163.20419912.905156.5143
9922.779151.58259929.361147.90069952.399136.77659962.272132.98729968.855129.8688
9972.146129.94589982.019 123.015 9985.31121.44459988.602120.51899991.893120.4788
9998.475121.659810011.64119.444710018.22119.3934 10024.8119.719110031.37 118.546
10034.66118.291910041.24119.634410070.84 127.96210093.87 137.42110110.31144.9332
10133.35156.342710143.22162.415510159.68171.961410162.97173.706910167.34175.5655
#Mann= 3 , 0 , 0
 9842.38    0.12       0 9842.38    0.12       010167.34    0.12       0
#XS Ineff= 2 , 0
       0                               0
Bank Sta=9842.38,10167.34
Exp/Cntr=0.3,0.1

Type RM Length L Ch R = 1 ,4858.185,49.815800,49.815800,49.815800
XS GIS Cut Line= 6
1190383.74686484  835372.70819311190371.42672142835171.097365652
1190366.53759447 835124.037347961190363.04569245835105.470283887
1190360.24949751835086.7932162961190337.50477479834840.526525959
#Sta/Elev= 30
9732.799232.38359775.321  216.29 9808.19201.31249821.338195.98719834.486189.9091
9873.929173.92359903.512161.07569929.808148.76679949.581140.6904 9952.88139.1817
9962.775 131.5139969.372127.13129972.671 127.1359979.268123.68869992.567113.8513
9995.899112.586710015.87115.427510038.96117.979910052.14 120.99610081.79130.4466
10098.27137.090510118.04146.191810150.98163.603510170.75174.9486 10203.7191.1463
10213.59194.982110230.06 202.74110246.53209.633510256.42215.4722 10267.2219.9715
#Mann= 3 , 0 , 0
9732.799    0.12       09732.799    0.12       0 10267.2    0.12       0
#XS Ineff= 2 , 0
       0                               0
Bank Sta=9732.799,10267.2
Exp/Cntr=0.3,0.1

Type RM Length L Ch R = 1 ,4808.369,49.815800,49.815800,49.815800
XS GIS Cut Line= 6
1190442.28112609835356.0334257341190429.48391839835155.478366503
1190420.46234752 835112.907111221190398.21798532  835065.4092944
 1190389.0618626 835030.170249011190367.03222671 834818.41733083
#Sta/Elev= 30
9726.812214.79249801.885188.43769815.024182.41789874.184159.4725 9930.25134.5611
9943.664129.78359953.726127.63369977.491117.0604 9981.01116.24339984.529116.6165
9995.533110.1056   10000108.191410002.97 108.44110006.61 111.00210010.26112.4953
 10013.9112.174110021.19114.887210024.77114.332510031.55115.414310055.28121.9241
10078.57131.715310098.43141.644810111.64146.782910121.53152.573610141.31161.6193
10167.67175.521710207.22192.2652 10223.7200.471410246.77 210.54510273.18220.7183
#Mann= 3 , 0 , 0
9726.812    0.12       09726.812    0.12       010273.18    0.12       0
#XS Ineff= 2 , 0
       0                               0
Bank Sta=9726.812,10273.18
Exp/Cntr=0.3,0.1

Type RM Length L Ch R = 1 ,4758.554,49.815700,49.815700,49.815700
XS GIS Cut Line= 6
1190465.07835107835352.044835875 1190454.1077561 835116.88493455
1190459.15920845 835053.238405491190458.82915356835006.733513787
 1190453.1667232834909.6447001741190443.89113746834806.676686571
#Sta/Elev= 30
9726.758210.30789745.277203.0826 9784.69189.38769807.681180.42239824.103174.8939
 9837.24168.83569870.084154.83279879.937149.97959889.791145.69199902.928141.4695
9929.203 129.8029942.341125.27939945.625125.30479958.763121.17639962.047119.8576
9971.893 114.6049978.457112.40159988.319110.2009 9998.24106.978910004.86106.0646
10034.49111.575210041.05114.241510060.74119.850110087.01128.524510103.44135.6648
 10113.3139.361910139.59151.1162 10205.4177.855810231.76 186.98410273.23199.2537
#Mann= 3 , 0 , 0
9726.758    0.12       09726.758    0.12       010273.23    0.12       0
#XS Ineff= 2 , 0
       0                               0
Bank Sta=9726.758,10273.23
Exp/Cntr=0.3,0.1

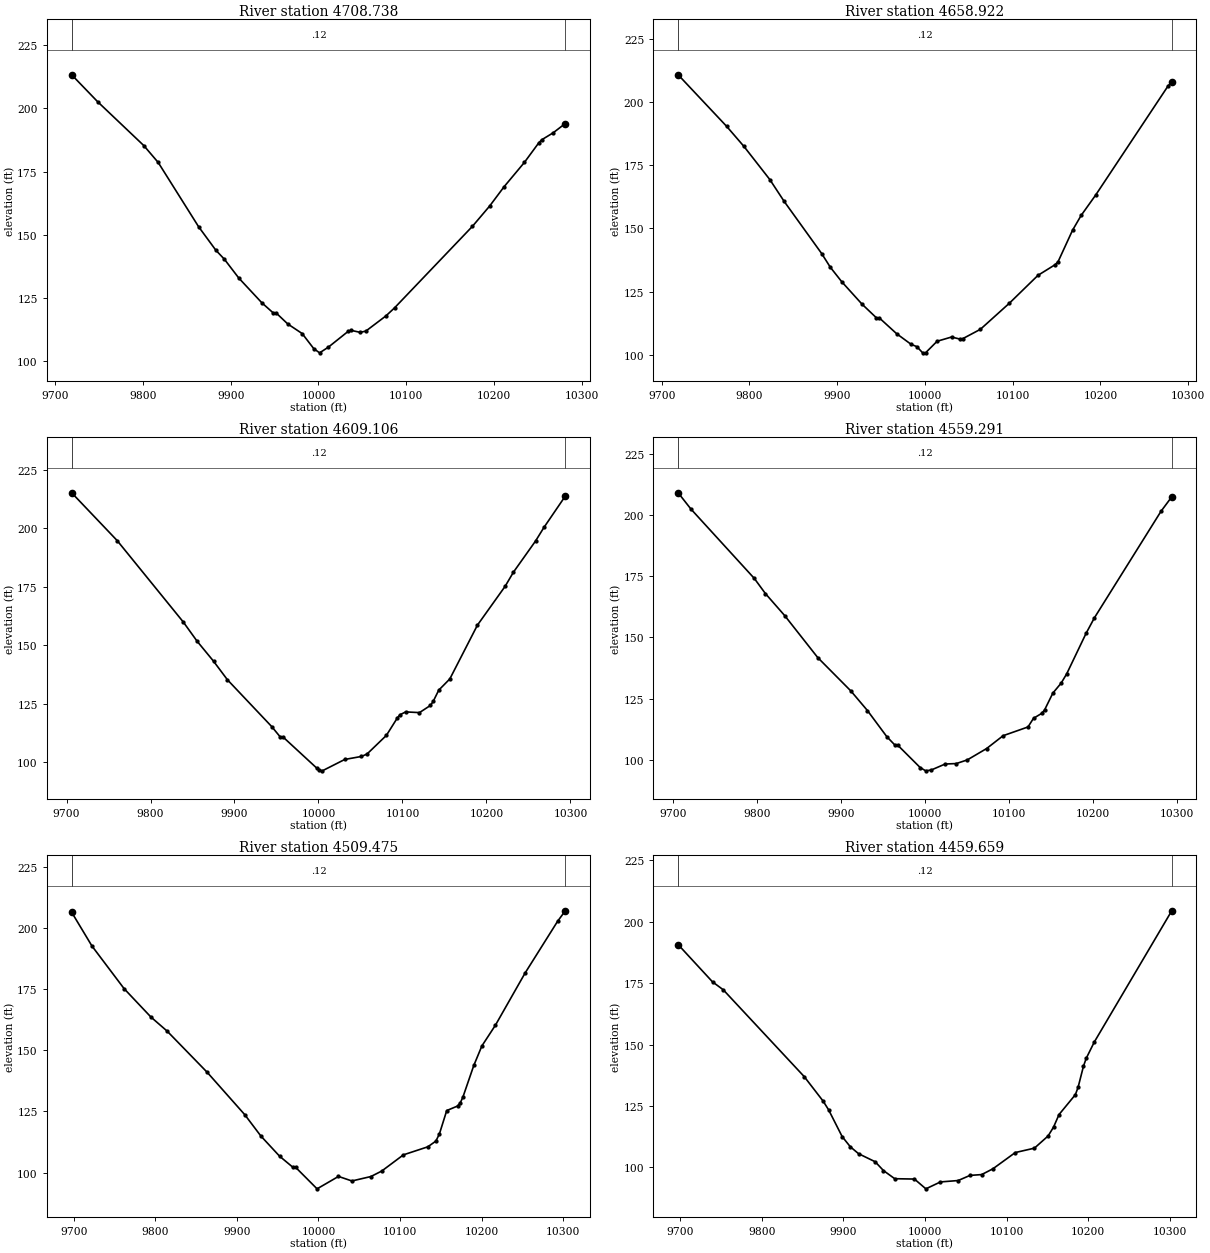
Type RM Length L Ch R = 1 ,4708.738,49.815800,49.815800,49.815800
XS GIS Cut Line= 6
1190511.20715836835366.5007123881190508.41213941835254.483258634
1190508.44239718835111.3132154091190503.26187396835065.714394998
1190499.87521533834911.7274497941190490.87464029834804.774572648
#Sta/Elev= 30
 9718.75213.33899748.433202.64149800.943185.30049817.352  178.619863.288153.2115
9882.973143.87969892.816140.2604 9909.22132.81149935.467123.0227 9948.59118.9552
9951.871118.95529964.994114.6378 9981.44110.82529994.638104.852810001.28103.1928
10011.18105.4183 10034.2111.803110037.48112.075710047.32111.323510053.88111.7788
10076.85 117.81810086.69121.003710175.34153.269810195.09 161.35410211.55169.0107
 10234.6178.602210251.06 186.38210254.35187.577410267.52190.371110281.25194.0335
#Mann= 3 , 0 , 0
 9718.75    0.12       0 9718.75    0.12       010281.25    0.12       0
#XS Ineff= 2 , 0
       0                               0
Bank Sta=9718.75,10281.25
Exp/Cntr=0.3,0.1

Type RM Length L Ch R = 1 ,4658.922,49.815800,49.815800,49.815800
XS GIS Cut Line= 6
1190546.82138092835362.5530782521190546.40343187835206.423669502
1190558.53567347835032.5632200081190560.35621897834977.514459644
1190557.81481166834897.9024060961190549.03673824 834800.93324108
#Sta/Elev= 30
9718.725210.75239773.988190.36389793.677182.43899823.209 169.3119839.615160.6429
9882.289140.04849892.154134.62259905.309128.83789928.329120.01219944.772114.5889
9948.061114.56269967.793108.32229984.236104.12839990.813103.2165 9997.39100.7731
10000.67100.769610013.83105.347510030.28107.022110040.15106.188610043.44106.4389
10063.15110.069810095.98120.3258 10128.8131.4232 10148.5135.670610151.78136.8746
10168.19149.260310178.04155.145710194.49163.148110276.85 206.22610281.26207.9721
#Mann= 3 , 0 , 0
9718.725    0.12       09718.725    0.12       010281.26    0.12       0
#XS Ineff= 2 , 0
       0                               0
Bank Sta=9718.725,10281.26
Exp/Cntr=0.3,0.1

Type RM Length L Ch R = 1 ,4609.106,49.815800,49.815800,49.815800
XS GIS Cut Line= 6
1190586.96805257835384.4121888931190587.65521547835196.331115791
1190611.80049312835051.2242267451190616.17793059834996.402190153
1190612.76640674834906.910442335 1190601.5867325834799.710544637
#Sta/Elev= 30
9706.116215.16999760.273  194.759839.039159.93049855.454151.73679875.152143.1385
9891.567135.25559944.397115.21039954.306110.87969957.609110.85119997.82897.53305
10001.1996.5379810004.5496.32611 10031.3101.191510051.21102.4814 10057.8103.5103
10080.84111.4708   10094118.992510097.29120.343410103.85121.514710120.26 121.216
10133.38124.300910136.66126.063510143.23130.824710156.38135.604410189.26158.6002
10222.25175.196710232.14181.240110258.53194.587210268.43200.341310293.87213.7385
#Mann= 3 , 0 , 0
9706.116    0.12       09706.116    0.12       010293.87    0.12       0
#XS Ineff= 2 , 0
       0                               0
Bank Sta=9706.116,10293.87
Exp/Cntr=0.3,0.1

Type RM Length L Ch R = 1 ,4559.291,49.815700,49.815700,49.815700
XS GIS Cut Line= 6
1190644.33590226835394.7261410011190641.22697551835216.186086893
1190656.81863756835067.2822807971190658.41507701 835021.85019236
 1190652.2587013834934.7552323671190637.31317482834809.015633587
#Sta/Elev= 30
9706.092209.03419721.351202.38849796.864174.05949809.988167.91639832.954158.9267
9872.324141.78889911.756128.16849931.486120.18019954.563109.51199964.491105.9895
  9967.8105.96419994.27496.91612 10000.995.5619210007.5195.9036410024.0598.34586
10037.2598.5288610050.38100.017110073.36 104.64510093.09109.903710122.69113.4632
10129.26116.998810139.13119.036110142.42120.397510152.29127.281410162.15131.3456
10168.74135.117110191.87151.680310201.78158.011910281.07201.474110293.88207.3803
#Mann= 3 , 0 , 0
9706.092    0.12       09706.092    0.12       010293.88    0.12       0
#XS Ineff= 2 , 0
       0                               0
Bank Sta=9706.092,10293.88
Exp/Cntr=0.3,0.1

Type RM Length L Ch R = 1 ,4509.475,49.815800,49.815800,49.815800
XS GIS Cut Line= 6
  1190714.601354835407.5931499941190702.30750873835197.883340979
1190702.15918388  835104.44256331190701.36483212835067.634396218
1190682.01472289834944.1855653551190662.59354861834805.815154993
#Sta/Elev= 30
9697.488206.44739722.365192.63759761.803175.17889794.668163.57769814.386157.8671
9863.683140.9562 9909.69123.63959929.375 114.9369952.341106.66859968.745102.1122
9972.026102.11249998.27393.3241910024.5398.4008610040.9796.5443510064.2298.35376
 10077.5100.591610104.07107.221510133.96110.505210143.92112.855210148.29115.8608
 10157.2125.339710170.47127.191110173.78128.463710177.09130.909410190.35143.7723
10200.29151.775610216.85160.239710253.29 181.61810293.05202.7327 10302.5207.0478
#Mann= 3 , 0 , 0
9697.488    0.12       09697.488    0.12       0 10302.5    0.12       0
#XS Ineff= 2 , 0
       0                               0
Bank Sta=9697.488,10302.5
Exp/Cntr=0.3,0.1

Type RM Length L Ch R = 1 ,4459.659,49.815800,49.815800,49.815800
XS GIS Cut Line= 6
1190804.29286957835398.4255341451190791.90186122835277.220792055
1190777.92392194835190.8843740281190755.35006156835112.503227715
1190711.29672672835001.7495612991190678.48782894834809.923243609
#Sta/Elev= 30
9697.502190.68179739.634175.52549752.826172.28899852.016136.97389875.281126.9644
9881.928123.45129898.546112.55379908.546108.4131 9918.69105.58889938.979102.3274
9949.16798.729499962.97195.421559987.12795.2820710001.1391.3006210018.9894.11183
10040.7194.67873 10055.296.7696110069.4697.0978910083.2499.4420310110.71106.0675
10134.16107.854210150.92112.810410157.62116.423510164.32121.531210184.33129.6079
10187.65132.576210194.29141.209510197.61144.376510207.56151.054210302.48 204.445
#Mann= 3 , 0 , 0
9697.502    0.12       09697.502    0.12       010302.48    0.12       0
#XS Ineff= 2 , 0
       0                               0
Bank Sta=9697.502,10302.48
Exp/Cntr=0.3,0.1

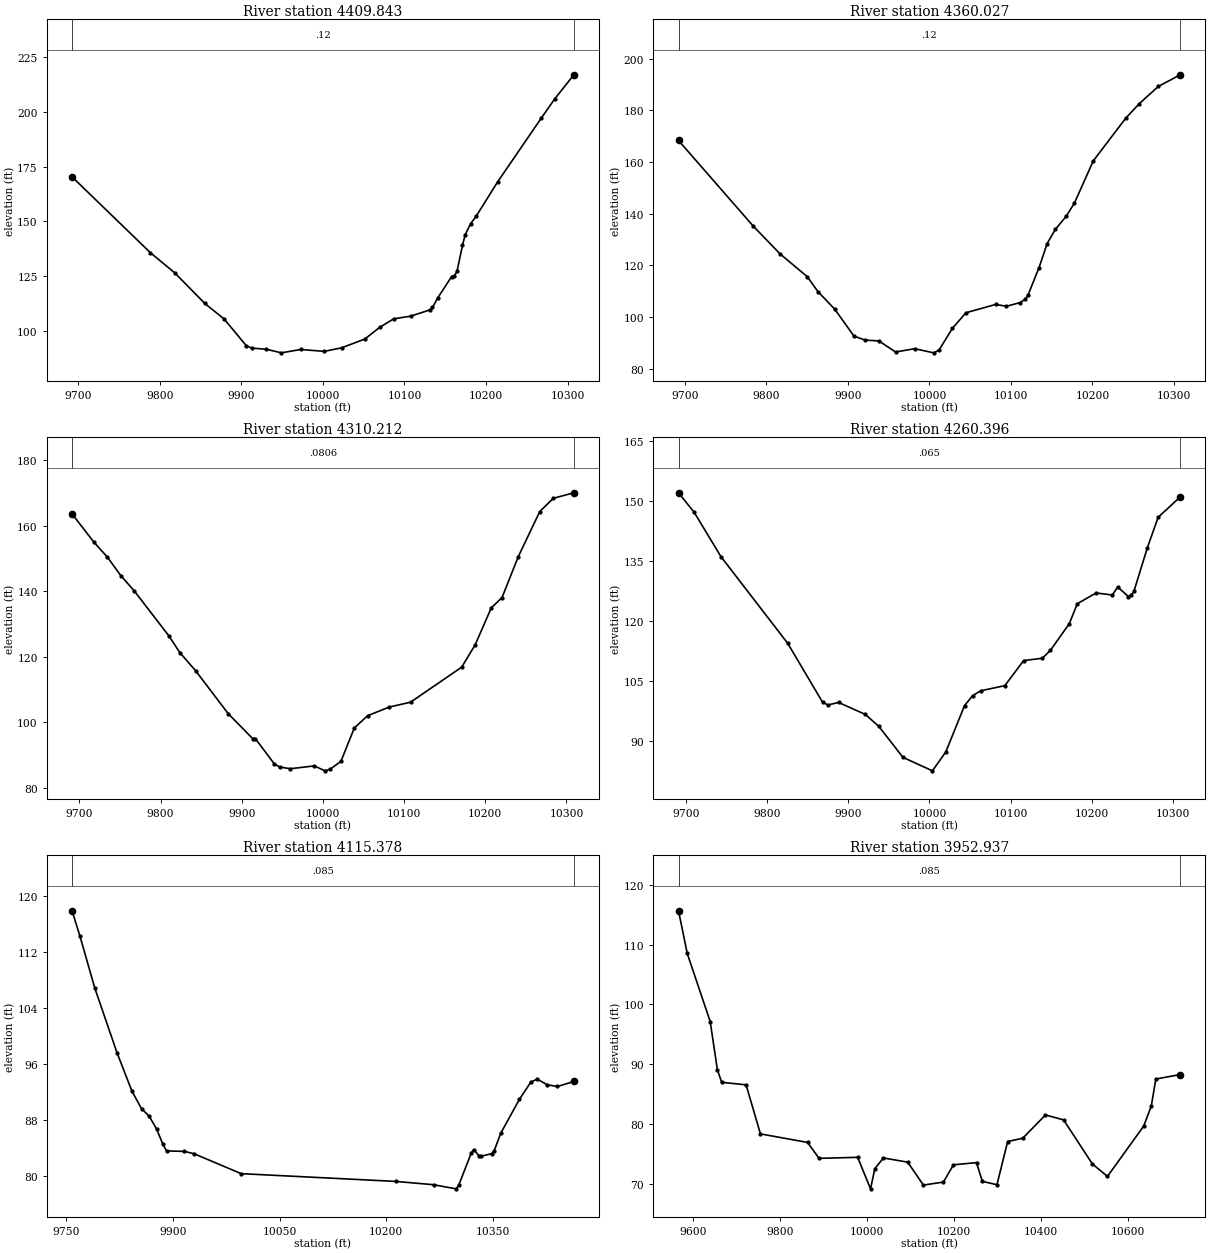
Type RM Length L Ch R = 1 ,4409.843,49.815800,49.815800,49.815800
XS GIS Cut Line= 6
1190866.76971298835353.5749928121190833.50259634 835151.80953101
1190807.57493782835092.1611113161190759.19851192835047.477747842
1190737.78616357835009.4797355261190692.40779642834778.755127167
#Sta/Elev= 30
9692.314170.33149788.498135.57989818.352 126.3659855.123112.38179878.809105.2732
9906.167 92.98249913.13391.939039930.54991.429959949.03789.784179972.62891.31892
10001.6490.4623910022.8892.0812610051.3696.1009610069.44101.4131 10086.8105.3658
10107.43106.558310130.97109.412610134.33110.593710141.06115.077910157.82 124.723
10161.14124.967810164.46127.179910171.11138.977110174.43143.842610181.08148.8851
10187.73152.216510214.32168.0856 10267.5197.081710284.12205.963810307.72217.0626
#Mann= 3 , 0 , 0
9692.314    0.12       09692.314    0.12       010307.72    0.12       0
#XS Ineff= 2 , 0
       0                               0
Bank Sta=9692.314,10307.72
Exp/Cntr=0.3,0.1

Type RM Length L Ch R = 1 ,4360.027,49.815700,49.815700,49.815700
XS GIS Cut Line= 6
1190879.05898351835352.0412909511190863.53719425835226.741288753
1190851.47733095835166.1827734791190826.21080356835073.704279895
1190817.45109607834991.2947122571190776.06024569834745.980226421
#Sta/Elev= 30
9692.243168.36889783.534135.35589816.682124.50889850.118115.67379863.499109.7962
9883.626103.16849907.43392.675729921.03891.120789938.04390.794359958.44986.51723
9982.079 87.790110005.1886.1872110011.7887.2491410028.2795.6912210044.77101.6968
10081.24104.914110094.55104.207410111.19105.626210117.84106.979610121.17 108.696
10134.48119.178310144.46128.503410154.44 133.94610167.75139.032510177.73144.0386
10201.02160.491310240.95177.055710257.58182.668510280.87189.303110307.79193.8044
#Mann= 3 , 0 , 0
9692.243    0.12       09692.243    0.12       010307.79    0.12       0
#XS Ineff= 2 , 0
       0                               0
Bank Sta=9692.243,10307.79
Exp/Cntr=0.3,0.1

Type RM Length L Ch R = 1 ,4310.212,49.815800,49.815800,49.815800
XS GIS Cut Line= 6
1190910.92862156835357.2144929391190897.49540272835232.162045988
1190875.46835437835092.0030682671190871.95121649835009.294681535
1190866.05892223834948.9369204161190835.59096427 834744.09252628
#Sta/Elev= 30
9690.917163.67889718.022154.9816 9734.52150.45329751.019144.81249767.517140.1633
9810.414126.34039823.657121.33259843.584115.61689883.437102.60589913.32795.05519
9916.64895.042319939.89687.374579946.53886.368299959.80985.826899989.38286.69452
10002.5285.1839510009.0985.7048310022.22 88.115810038.63 98.2776 10055.1102.0419
10081.47104.651910107.88106.1522 10170.9116.853710187.49123.667810207.39134.9772
10220.66138.131210240.56150.576410267.09164.386710283.68168.435310309.11170.1309
#Mann= 3 , 0 , 0
9690.917  0.0806       09690.917  0.0806       010309.11  0.0806       0
#XS Ineff= 2 , 0
       0                               0
Bank Sta=9690.917,10309.11
Exp/Cntr=0.3,0.1

Type RM Length L Ch R = 1 ,4260.396,145.017600,145.017600,145.017600
XS GIS Cut Line= 6
1190951.73449749 835352.898782711190940.02285047835198.590915213
1190922.83454056835046.1858115551190920.73520941835025.386243473
1190897.90297191834847.1158797481190880.82697587834738.958279028
#Sta/Elev= 30
9690.877152.00689710.286147.07839743.188136.00899825.445114.31449868.29799.59258
  9874.998.892779888.10699.522099921.12396.511489937.63193.545069967.34685.78931
10003.6682.4070310020.1587.12953 10043.398.7567410053.22101.216610063.15102.4444
10092.91103.731610116.07110.003610139.22110.590610149.14 112.583 10172.3119.2312
10182.22 124.247 10205.4126.925510225.33126.423410231.97128.426310245.26126.0108
10248.58126.4257 10251.9127.298110268.51138.251810281.79145.868410309.13150.9901
#Mann= 3 , 0 , 0
9690.877   0.065       09690.877   0.065       010309.13   0.065       0
#XS Ineff= 2 , 0
       0                               0
Bank Sta=9690.877,10309.13
Exp/Cntr=0.3,0.1

Type RM Length L Ch R = 1 ,4115.378,162.441100,162.441100,162.441100
XS GIS Cut Line= 5
1190983.65958798835262.044472888 1191050.5585455835069.024529845
 1191090.0398975834972.5145583451191165.71248877834766.334164679
1191097.03312781 834603.67483677
#Sta/Elev= 30
9758.663117.81739769.796 114.167 9790.63106.76319821.88197.513439842.71492.05644
9856.26289.532059867.02188.479449877.43786.618829886.31784.434369891.32783.51594
9916.37383.441289929.52283.129039996.17580.2630410213.0779.1574110266.2878.68483
10297.9478.0943810301.5978.5800410319.31 83.214310322.8783.7061110329.9982.83198
10333.5582.75253 10347.883.1210610351.3683.4928610360.6386.0211310386.9790.87919
10402.8193.31821 10411.993.7774510426.1492.9504410440.3992.7177210463.4193.43059
#Mann= 3 , 0 , 0
9758.663   0.085       09758.663   0.085       010463.41   0.085       0
#XS Ineff= 2 , 0
       09936.518        10047.91       0
Bank Sta=9758.663,10463.41
Exp/Cntr=0.3,0.1

Type RM Length L Ch R = 1 ,3952.937,196.607600,196.607600,196.607600
XS GIS Cut Line= 6
1191190.93668589835484.6754298961191209.54033071835298.162347123
1191222.07750142835015.5094116781191221.83752829834871.481288612
1191207.06965426834769.248057619 1191064.4810445834358.449142307
#Sta/Elev= 30
9567.102115.64749587.097108.51069639.85197.141779656.33689.093619666.22886.98513
9722.279 86.56599755.24678.36969 9863.5976.939779889.87374.282989978.57874.45491
10008.1569.18924   1001872.5512110037.71 74.3469 10093.573.6500210129.5969.81677
10175.5770.3199510198.6673.2031910251.6373.5712110264.9670.4399110298.4969.87997
10323.1677.0926910357.8877.6487710409.9881.5292610451.6580.7085510517.6473.36299
10552.3671.2617210635.7179.6816610653.0883.02012 10663.587.5354610719.7988.28533
#Mann= 3 , 0 , 0
9567.102   0.085       09567.102   0.085       010719.79   0.085       0
#XS Ineff= 2 , 0
       0 9931.77        10067.04       0
Bank Sta=9567.102,10719.79
Exp/Cntr=0.3,0.1

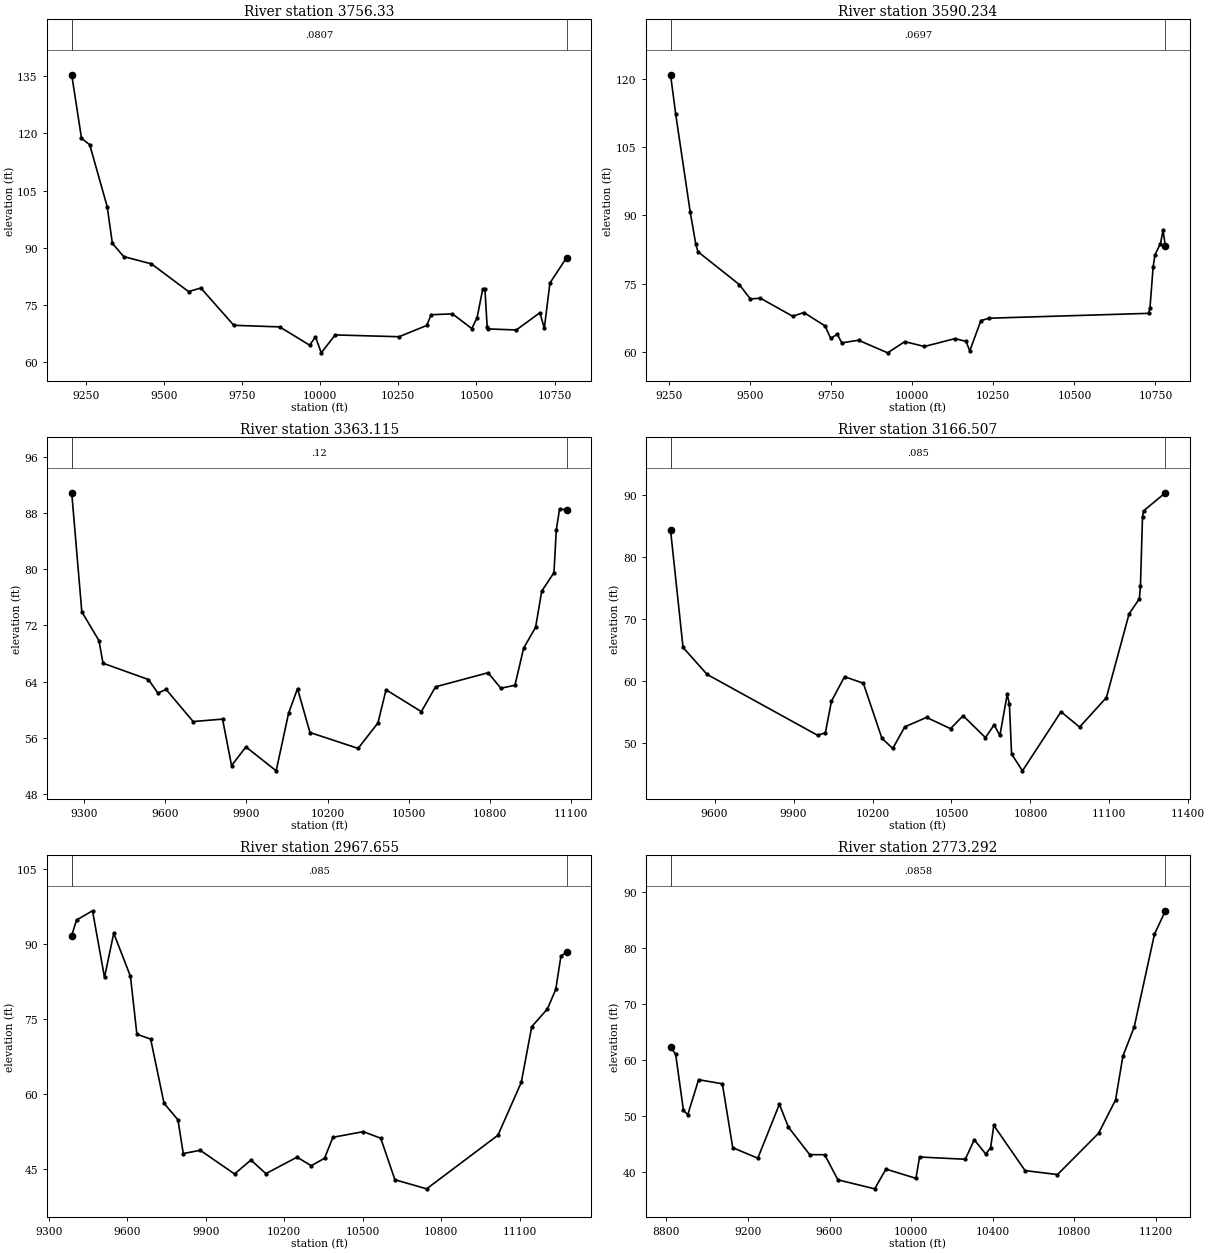
Type RM Length L Ch R = 1 , 3756.33,166.095200,166.095200,166.095200
XS GIS Cut Line= 6
1191529.14116731835850.2526946661191477.16842625835232.540846318
1191436.16495663835117.489250153 1191365.7870506834996.554947391
1191297.86314842 834806.606990741191097.03312781834349.768586755
#Sta/Elev= 30
9205.301135.36249236.554118.72819262.894117.00829318.865100.74559335.32791.16237
9371.54487.680889460.43985.761739578.96678.504449618.47679.427739723.83369.65736
9870.78369.235119966.60264.431529985.22666.6262910003.63 62.4319 10048.267.13054
10252.5966.6563810341.0569.6087910355.38 72.426710423.4772.6555510485.3668.79136
10502.3271.6578110520.2479.1568510527.4179.0796510534.5769.1369410538.1668.70081
10627.7568.4342110703.0272.9469110717.3568.8992710735.2780.7484910788.5187.39695
#Mann= 3 , 0 , 0
9205.301  0.0807       09205.301  0.0807       010788.51  0.0807       0
#XS Ineff= 2 , 0
       09936.971         10111.2       0
Bank Sta=9205.301,10788.51
Exp/Cntr=0.3,0.1

Type RM Length L Ch R = 1 ,3590.234,227.119900,227.119900,227.119900
XS GIS Cut Line= 5
1191777.45513636835683.3189339791191602.17468765835122.004163682
 1191518.7078073 834927.943666891191414.37420687834750.576546162
1191111.80676562834326.982128426
#Sta/Elev= 30
9254.911120.90779270.759112.26619315.44190.758759332.62683.694559339.50181.98668
9466.67274.781019501.04371.614929531.97771.768349631.42567.803199666.02268.62525
9731.32765.662039748.51262.961699769.135 63.82589782.88361.949799834.43962.52876
 9924.1859.755759976.96362.2185610037.6861.1538910131.7562.8837710166.0162.27433
10177.43 60.192410211.6866.8458110237.5967.3723410728.93 68.443510732.96 69.6431
10742.8278.7376210748.4681.31286 10765.4 83.798210773.2886.7089610780.54 83.1552
#Mann= 3 , 0 , 0
9254.911  0.0697       09254.911  0.0697       010780.54  0.0697       0
#XS Ineff= 2 , 0
       09861.152        10079.29       0
Bank Sta=9254.911,10780.54
Exp/Cntr=0.3,0.1

Type RM Length L Ch R = 1 ,3363.115,196.607600,196.607600,196.607600
XS GIS Cut Line= 6
1191908.91547287835520.558517292 1191726.5608761835155.068143383
 1191675.9380056834948.7596429741191671.36834306834750.379282594
1191398.68243337 834430.063725651190919.08173895834089.351920098
#Sta/Elev= 30
9253.73690.864449291.05273.933099354.48169.843979369.40566.623989537.304 64.3035
9572.54962.377329602.67462.891889702.83658.327089811.44758.674319844.78952.06356
9897.90754.7244810009.7451.3178610055.7459.5239510088.6363.0111510134.7156.77006
10312.6854.5090210385.9258.1165410416.0962.8440510546.6359.7358210598.9563.26776
10793.3765.2699710840.4163.0674210892.7363.4885810924.9368.7745710969.1971.74745
10991.6476.8685911036.9679.4963411045.6685.6000611057.7388.5675911083.5988.42875
#Mann= 3 , 0 , 0
9253.736    0.12       09253.736    0.12       011083.59    0.12       0
#XS Ineff= 2 , 0
       09732.032        10062.78       0
Bank Sta=9253.736,11083.59
Exp/Cntr=0.3,0.1

Type RM Length L Ch R = 1 ,3166.507,198.851800,198.851800,198.851800
XS GIS Cut Line= 6
 1192004.2880075835458.0958983051191821.49221847835043.738225854
1191805.42087415834924.1066837691191817.86820485834825.910734081
1191400.85257223834284.6644200981190962.48451671 833998.20608677
#Sta/Elev= 30
9432.55984.332519479.98965.38186 9571.4661.025389991.25851.1940210020.8451.58446
10043.9456.6954610093.7160.6556510165.1959.59894 10235.650.7137110277.0249.06506
10322.5852.5544510405.41 54.079610496.5352.2577910544.3254.3573410629.0650.81969
 10662.252.8707110684.0951.16235 10711.957.7917510720.1856.2591310728.4648.18003
10769.8845.44913 10916.454.9954910986.9552.5190311088.8557.2868911175.0770.81115
11214.2673.2561811218.1875.3159711226.0286.4543811229.9487.4408211313.01 90.3659
#Mann= 3 , 0 , 0
9432.559   0.085       09432.559   0.085       011313.01   0.085       0
#XS Ineff= 2 , 0
       09859.358        10110.54       0
Bank Sta=9432.559,11313.01
Exp/Cntr=0.3,0.1

Type RM Length L Ch R = 1 ,2967.655,194.363300,194.363300,194.363300
XS GIS Cut Line= 6
1192369.26758636835266.1096379331191997.10161695834862.507476842
1191926.02618334834772.9456700981191633.05743337834471.296364546
1191459.44632223834249.9421978591191027.58868334833950.463031203
#Sta/Elev= 30
9387.86691.678219406.167 94.78679467.29996.635529513.14983.312239548.36992.15367
9612.28483.530599636.88871.947679689.50170.990869740.69658.143739793.70954.85548
 9814.1748.104469878.97148.7533110010.1644.0263310072.6646.8068910129.8444.09303
10248.7547.37639 10303.4 45.675710353.9447.1587710385.9651.3531910501.97 52.4796
10568.7351.1701910622.8942.8711810744.1741.0505611016.53 51.764311105.7762.33483
 11145.773.4672911205.5977.0077411237.5380.9202711257.49 87.623511278.8688.30882
#Mann= 3 , 0 , 0
9387.866   0.085       09387.866   0.085       011278.86   0.085       0
#XS Ineff= 2 , 0
       09860.017        10075.35       0
Bank Sta=9387.866,11278.86
Exp/Cntr=0.3,0.1

Type RM Length L Ch R = 1 ,2773.292,196.607600,196.607600,196.607600
XS GIS Cut Line= 6
1192933.47142908835435.0049649631192514.37739661834923.274086758
1192315.81529227834781.1722148361191719.86298895834438.744281203
1191457.27618337834171.8171978591191079.67201668833913.570670098
#Sta/Elev= 30
8819.89862.283218845.02360.973848883.189 50.93858904.39350.192218957.43656.43867
 9074.0255.712769124.90844.291839247.88842.407719353.90552.06204 9397.5747.98718
9502.39643.051829576.09243.03007 9640.6638.547569821.18936.934549876.55640.46015
10023.5738.8126210041.44 42.623310265.6142.2223410309.7345.7045310365.8843.16071
10389.9544.27033 10405.548.2774410558.8140.1997410717.8739.4840710919.4846.86384
11002.95 52.824511038.7260.6461511094.3765.8747811193.7482.4516211247.3186.63431
#Mann= 3 , 0 , 0
8819.898  0.0858       08819.898  0.0858       011247.31  0.0858       0
#XS Ineff= 2 , 0
       0  9862.2        10101.22       0
Bank Sta=8819.898,11247.31
Exp/Cntr=0.3,0.1