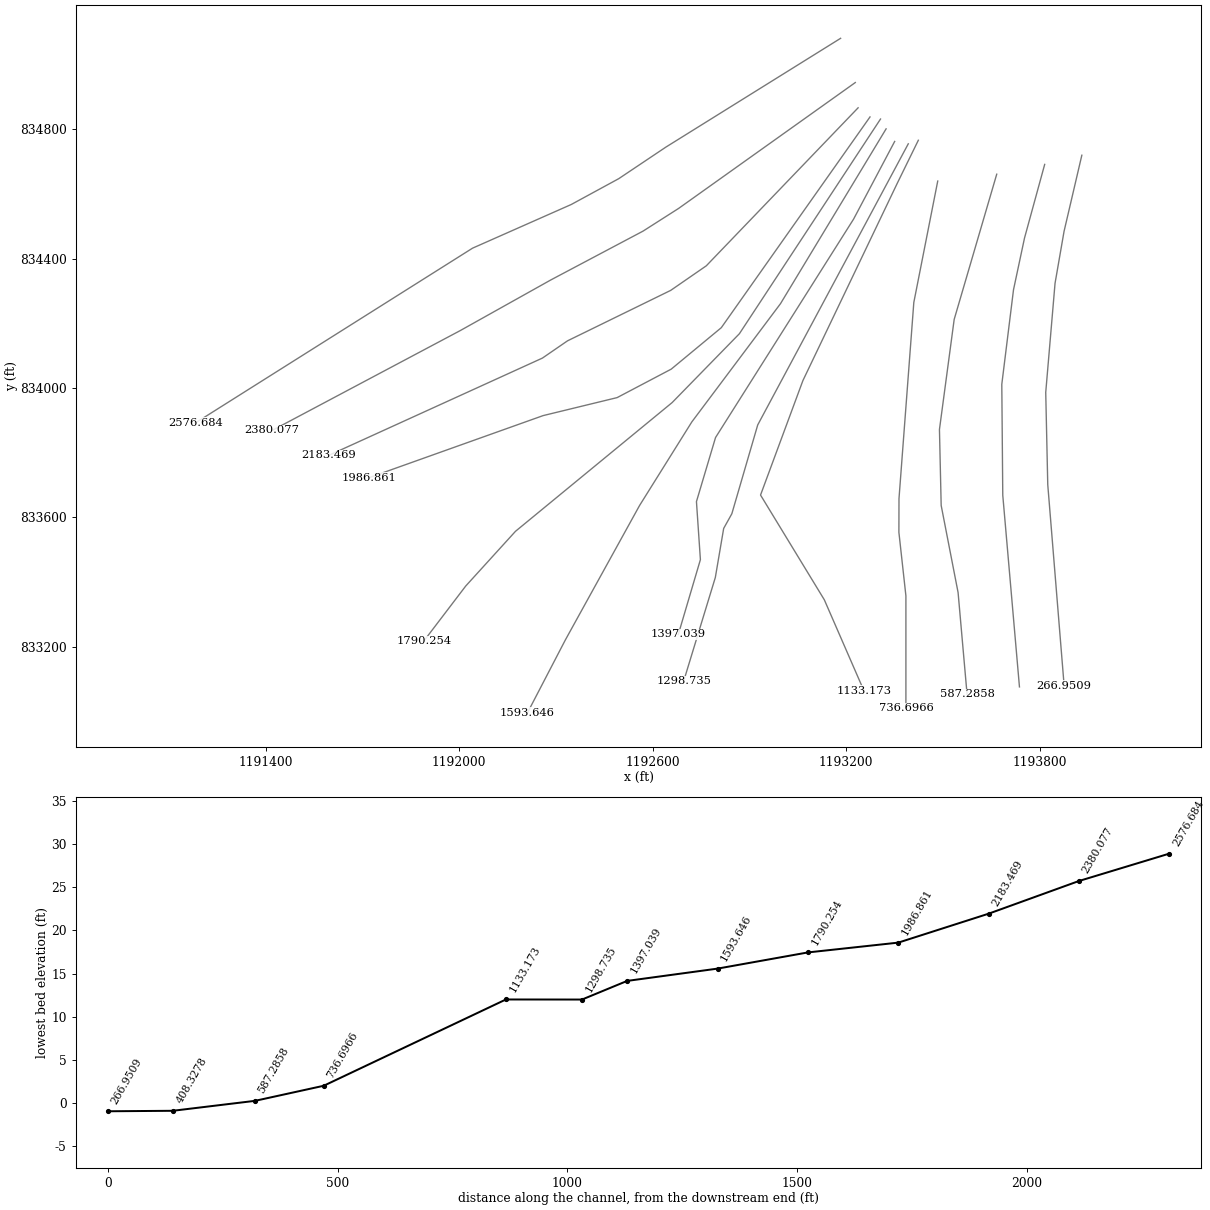
HEC-RAS study 79_ras.prj: 79

--- 79_ras.g01 (geometry) --- (continued)

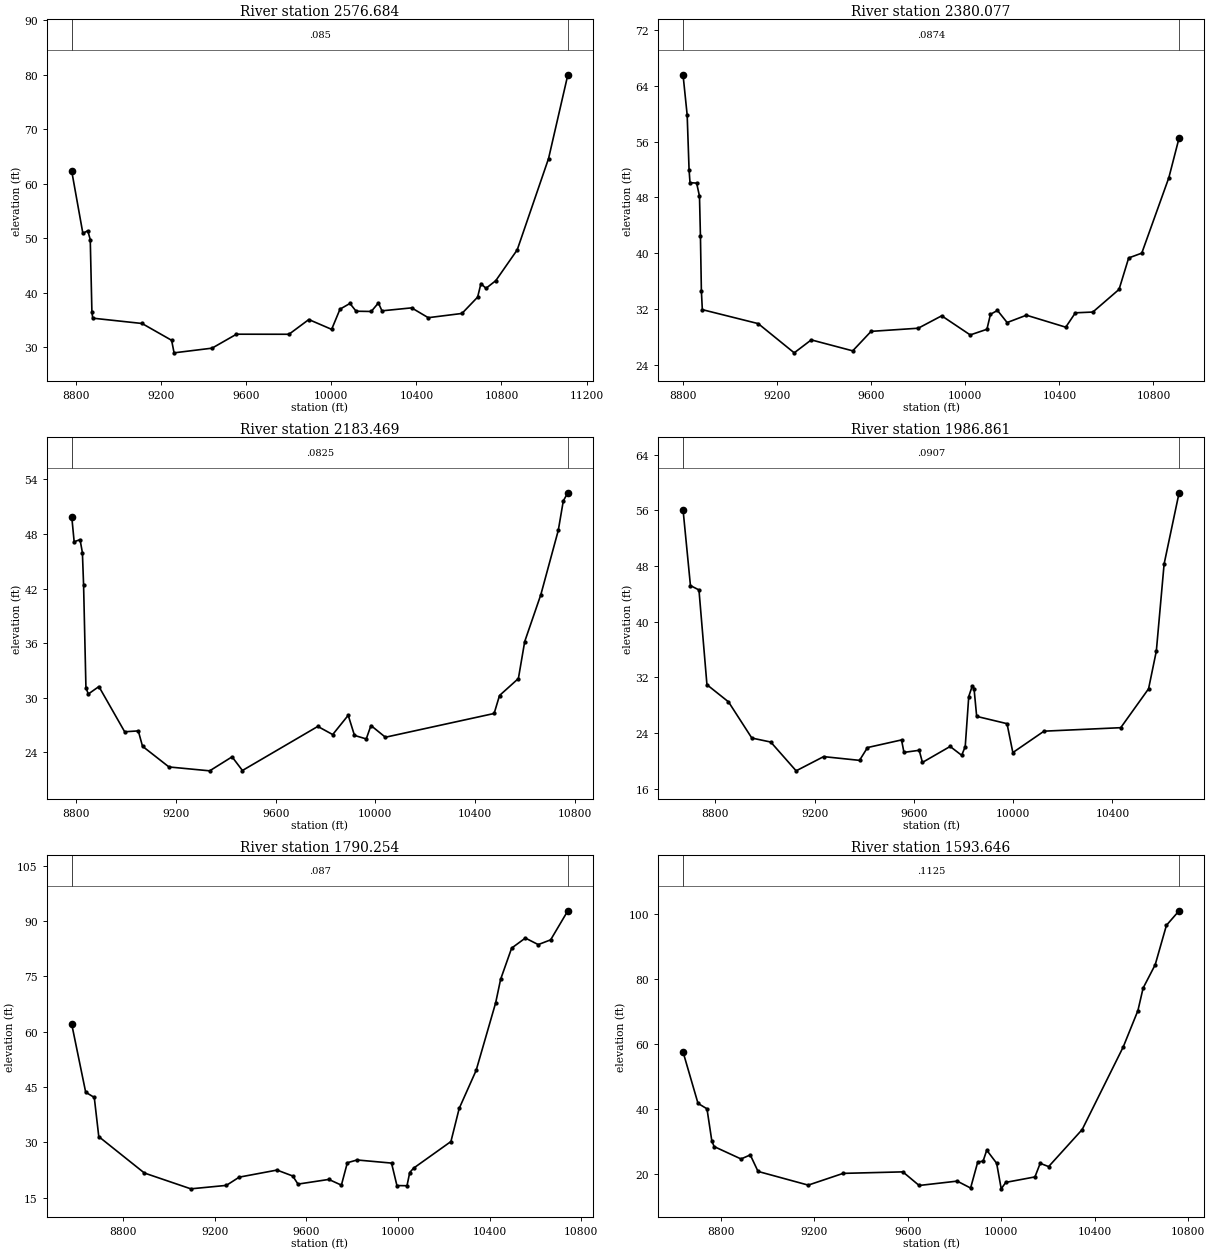
Type RM Length L Ch R = 1 ,2576.684,196.607600,196.607600,196.607600
XS GIS Cut Line= 6
1193182.53660002835081.1053923071192640.79362416834744.787112504
1192494.63900161834647.1917846351192347.34622955834567.341890752
1192041.29052538834432.3194323481191181.66854447833891.869281217
#Sta/Elev= 30
8780.97862.243638833.021 50.89298856.19151.350148867.77649.730798875.49936.50623
8879.361  35.294 9111.0634.317459250.079 31.22769261.66428.924339440.06629.78398
9554.89232.349059801.56132.336239894.82935.0423110002.0333.2375310041.3636.94966
10088.0237.9988710116.9336.5711610188.1136.5230610221.7238.0893510238.4936.64341
   1037837.1870810455.9535.38208 10614.436.1600310688.0339.1612810703.5341.65259
10727.1740.7719910773.2942.1827710874.0547.8417711021.31 64.622711111.9580.00925
#Mann= 3 , 0 , 0
8780.978   0.085       08780.978   0.085       011111.95   0.085       0
#XS Ineff= 2 , 0
       09832.036         10084.2       0
Bank Sta=8780.978,11111.95
Exp/Cntr=0.3,0.1

Type RM Length L Ch R = 1 ,2380.077,196.607500,196.607500,196.607500
XS GIS Cut Line= 6
1193228.10951671834944.3866423221192680.19315869834555.167510748
1192569.94081217834485.0308057221192284.21048412834334.203506202
1192003.38948077834177.6449711171191420.10480323833868.887317672
#Sta/Elev= 30
8801.38865.580458818.96659.814828827.01451.983658831.03950.125238859.20950.05992
8871.28248.187918875.30742.483118879.33134.616588883.35531.932249120.79329.93032
9273.71825.744919346.157 27.60089522.261 26.02959600.24728.82147 9800.58 29.2724
9900.23431.0504310021.5228.3097510092.4529.1194310107.3731.2630910137.2231.81988
10178.2530.0846210260.2531.13754 10427.329.4204910468.1331.4792610542.3731.58838
10653.7434.8331710694.5739.3383610750.25 40.028710865.3350.8471610908.8156.53692
#Mann= 3 , 0 , 0
8801.388  0.0874       08801.388  0.0874       010908.81  0.0874       0
#XS Ineff= 2 , 0
       09837.557        10161.34       0
Bank Sta=8801.388,10908.81
Exp/Cntr=0.3,0.1

Type RM Length L Ch R = 1 ,2183.469,196.607600,196.607600,196.607600
XS GIS Cut Line= 6
1193236.79007223834866.2616423221192766.07172081834377.769909739
1192655.73736501834301.8199163231192335.71593156834145.802764311
1192257.99594203834092.5229969621191596.16507226833792.042892307
#Sta/Elev= 30
8781.92949.86911 8791.4547.147938815.09147.383618824.547 45.95198829.27642.40307
8838.73231.083438848.18830.396998890.74231.218418994.11726.243629048.79126.34167
9065.68624.650839171.80822.373869335.19421.94678 9425.0323.487519466.56921.98356
9768.98926.834069828.72525.937449890.98628.057979916.09525.84711 9963.3425.45506
9982.18526.9335310040.2125.6435810476.4128.2573310498.0330.2344110573.73 32.0994
10599.0836.1678510663.8441.3320910733.7448.3963210753.9651.6478510772.1652.53769
#Mann= 3 , 0 , 0
8781.929  0.0825       08781.929  0.0825       010772.16  0.0825       0
#XS Ineff= 2 , 0
       0    9837         10236.7       0
Bank Sta=8781.929,10772.16
Exp/Cntr=0.3,0.1

Type RM Length L Ch R = 1 ,1986.861,196.607600,196.607600,196.607600
XS GIS Cut Line= 6
1193273.68243334 834838.049836771192812.59053028834186.495308921
1192657.40074295834058.4034381811192489.69351077833970.358073637
1192260.10380271833914.6736967271191719.86298895833722.598447859
#Sta/Elev= 30
 8669.6156.091178699.47545.185478733.80844.560098765.96230.952428852.82228.49119
8946.82923.295849023.19522.717749125.43818.585869236.21720.62672 9380.9120.09029
9413.06421.929149550.22123.023129560.01421.233819621.43821.535799634.46419.79468
9746.17622.086749792.668 20.81259806.94122.06698 9821.1429.252539835.33930.77874
9842.43930.401469853.08826.404869975.39625.358689998.84821.20874 10124.524.28116
10433.6824.7817510545.8230.3628910577.1635.78412 10608.548.28639 10668.958.50985
#Mann= 3 , 0 , 0
 8669.61  0.0907       0 8669.61  0.0907       0 10668.9  0.0907       0
#XS Ineff= 2 , 0
       09832.377        10280.28       0
Bank Sta=8669.61,10668.9
Exp/Cntr=0.3,0.1

Type RM Length L Ch R = 1 ,1790.254,196.607500,196.607500,196.607500
XS GIS Cut Line= 6
1193306.23451671834831.5394200831192868.76524502 834167.91795902
1192660.23870432833955.0261280691192174.44317198833556.962921038
1192020.09922275833387.7469665111191889.90369886 833217.28715013
#Sta/Elev= 30
8576.15461.959148636.83943.614718674.34742.200958693.99531.591898893.16121.72989
9095.83417.447619250.81918.380769307.00620.613439472.02822.53056 9540.6420.92666
9563.59918.730289698.21119.99757 9753.0518.447419779.03924.515659821.556 25.2647
9971.91524.421739995.50518.3359410039.42 18.288410051.3821.8712310068.01 23.0392
10231.2130.25785 10267.339.2328610341.25 49.522610426.4867.8297410448.0774.18734
10496.1982.6420210556.0285.3687410612.3383.5968110666.5384.8871310741.5792.75549
#Mann= 3 , 0 , 0
8576.154   0.087       08576.154   0.087       010741.57   0.087       0
#XS Ineff= 2 , 0
       09814.025                       0
Bank Sta=8576.154,10741.57
Exp/Cntr=0.3,0.1

Type RM Length L Ch R = 1 ,1593.646,196.607600,196.607600,196.607600
XS GIS Cut Line= 6
1193323.59562778834801.1574756351192996.08506614 834260.65556021
1192721.26943675833895.2752365321192559.23401609 833636.86401239
1192329.03555322 833221.075353191192211.38491833832995.433049038
#Sta/Elev= 30
8637.16357.686378701.33341.846998739.69540.186588760.43930.303368770.384 28.5631
8885.46824.757818925.04225.997698958.35420.920759173.17816.710799322.67820.32295
9578.31920.786559648.15116.599469811.11717.939789868.43615.813969898.98423.80634
9921.89424.08386 9937.5927.456249979.98323.436839999.533  15.56710019.1217.55454
10143.9619.2350710166.4323.4144410202.6122.4097410346.1633.7966910521.9659.20998
10584.8670.3936510607.0677.3071910658.8684.4968910706.96 96.618910761.19101.0907
#Mann= 3 , 0 , 0
8637.163  0.1125       08637.163  0.1125       010761.19  0.1125       0
#XS Ineff= 2 , 0
       09933.258                       0
Bank Sta=8637.163,10761.19
Exp/Cntr=0.3,0.1

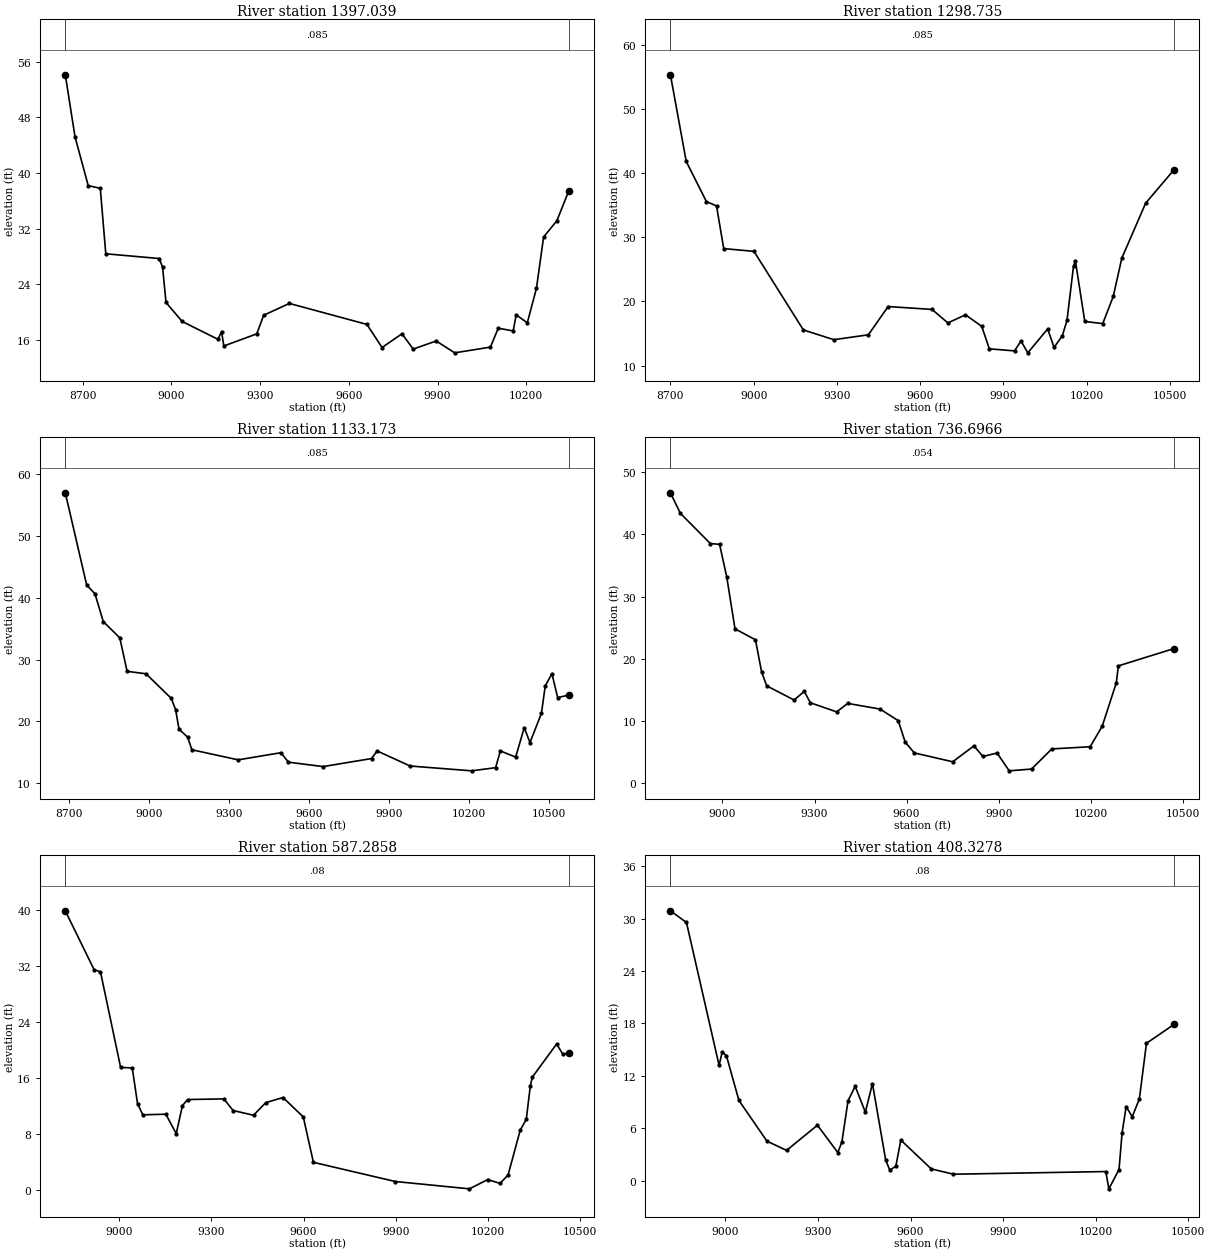
Type RM Length L Ch R = 1 ,1397.039,98.303800,98.303800,98.303800
XS GIS Cut Line= 6
  1193350.149084834762.2649253161193222.68145239834521.976149589
 1192794.7441408833846.9033932391192735.55381814833648.834249526
1192747.80251649833469.3909671011192679.24394509833238.040658087
#Sta/Elev= 30
8640.807 54.11318673.761 45.19458718.328 38.1824 8759.1837.791838777.785  28.381
  8958.127.69924 8969.7826.475678981.45921.383519035.96218.653039157.33916.08504
9169.20917.198939177.12315.125279288.33416.86886 9311.8119.542719398.705 21.2435
9661.02218.225919712.19714.906689779.46916.881099817.51814.681859895.26715.84409
9957.95614.1406310078.7514.9639810105.1817.6847810155.6217.2886610165.8119.59818
10203.4218.46348 10234.323.4052710258.5130.7850210303.4633.1366210343.9637.44932
#Mann= 3 , 0 , 0
8640.807   0.085       08640.807   0.085       010343.96   0.085       0
#XS Ineff= 2 , 0
       09854.963        10106.87       0
Bank Sta=8640.807,10343.96
Exp/Cntr=0.3,0.1

Type RM Length L Ch R = 1 ,1298.735,165.561700,165.561700,165.561700
XS GIS Cut Line= 6
1193392.34609488834754.9263147261192925.53263113833885.882132635
1192845.23313475833611.1322537811192819.97343203 833565.95016627
1192794.10642743833414.2600295391192695.91313544833093.712826386
#Sta/Elev= 30
8699.91955.353328756.86441.840598829.70135.577348866.11934.889938892.09728.23792
9001.22527.804689179.20615.548089289.02414.026849413.534 14.78859484.83619.19768
9642.89318.748449700.27416.643479763.641 17.90969822.32416.107499849.623 12.6005
9940.40612.279999963.87513.819469988.29111.9754910059.9615.7049810083.1112.82635
10112.9814.6548910129.6217.0353710153.1825.4939210159.92 26.333810193.78 16.8669
10258.5916.5359110296.3920.7712810327.3326.7529810413.2835.3299610515.4140.53329
#Mann= 3 , 0 , 0
8699.919   0.085       08699.919   0.085       010515.41   0.085       0
#XS Ineff= 2 , 0
       09864.603        10104.82       0
Bank Sta=8699.919,10515.41
Exp/Cntr=0.3,0.1

Type RM Length L Ch R = 1 ,1133.173,396.476700,396.476700,396.476700
XS GIS Cut Line= 6
 1193423.5351899834765.9342306261193358.81582421834634.156690881
 1193065.6091063 834022.93345575 1192934.2728343833669.046440899
1193132.08516553833345.165139571 1193254.8527095833064.069797456
#Sta/Elev= 30
8686.67656.978098767.05942.020588797.81840.656338829.19636.131168891.07533.50619
  8918.528.085368989.32327.691979083.93123.716749100.55121.872649113.04218.74508
9145.79117.413839161.23515.396559335.00813.763649495.11514.916949523.73413.38499
9653.21512.671659835.18913.973869856.18515.202159979.82812.7648310210.4911.98382
10300.3912.4967810318.2915.2110810375.5714.2044310407.7918.9680910429.2716.56122
10472.2421.2794610486.5625.7258210511.6227.70482 10533.123.8376610575.1224.24001
#Mann= 3 , 0 , 0
8686.676   0.085       08686.676   0.085       010575.12   0.085       0
#XS Ineff= 2 , 0
       09821.438        10107.48       0
Bank Sta=8686.676,10575.12
Exp/Cntr=0.3,0.1

Type RM Length L Ch R = 1 ,736.6966,149.410800,149.410800,149.410800
XS GIS Cut Line= 6
1193483.70234973834639.8114713951193409.52976779834264.536620769
1193363.54664774833657.7874320681193363.25149685833553.845566227
1193384.98227427833357.6314769011193385.01138775833009.832928074
#Sta/Elev= 30
8830.50146.71371 8862.7243.415928960.56838.544338990.71738.413529014.16133.11878
9040.95324.809839107.61723.053819127.59917.87632 9144.2115.63844 9233.6113.36025
  9266.614.754349286.39412.919799372.08111.453149408.24112.813279513.43211.90342
9572.60210.043049595.612 6.568979625.1974.8420229750.2133.4196259819.3025.970855
9848.8544.2729979894.8134.8302869934.245 1.96125 10007.12.24955810073.175.488782
10198.015.83961710237.399.14692110283.32 16.135610289.8818.8524410471.23 21.6407
#Mann= 3 , 0 , 0
8830.501   0.054       08830.501   0.054       010471.23   0.054       0
#XS Ineff= 2 , 0
       09635.276        10103.96       0
Bank Sta=8830.501,10471.23
Exp/Cntr=0.3,0.1

Type RM Length L Ch R = 1 ,587.2858,178.958000,178.958000,178.958000
XS GIS Cut Line= 6
1193666.61075449834661.0374160611193534.67509801834212.074371769
1193489.01217433833871.8630477811193494.36439119833636.882557866
1193546.81518627833367.6055781811193574.62884392833053.056218806
#Sta/Elev= 30
8825.00639.875128918.67731.474798939.47831.156149005.00117.526999042.80317.46181
9059.98312.356859077.04110.766259152.02410.860949185.7938.0829059206.05412.09491
9222.93812.949049340.69513.043789370.71811.385749437.17810.70987    9477 12.5106
9533.11913.233339598.99410.468269631.8783.9922159898.1681.25797210139.360.211382
10198.85 1.5362810238.460.98965210264.872.17451710304.468.58050410324.1910.12361
10337.3414.9274310343.9216.1497110422.8420.8751910442.5719.4475710462.6119.55793
#Mann= 3 , 0 , 0
8825.006    0.08       08825.006    0.08       010462.61    0.08       0
#XS Ineff= 2 , 0
       09627.987        10199.88       0
Bank Sta=8825.006,10462.61
Exp/Cntr=0.3,0.1

Type RM Length L Ch R = 1 ,408.3278,141.376900,141.376900,141.376900
XS GIS Cut Line= 6
1193815.30463966834691.2822793911193752.74512411834463.631785755
1193718.63858702834303.8925219171193682.31178861834011.437276601
1193685.33600519833668.6004500721193737.07969447833075.936620288
#Sta/Elev= 30
8821.69230.904458873.71729.562928979.42813.206798989.58514.711229003.12814.31805
9043.7579.1789759134.6824.5165959198.2873.4611729298.2146.3421869364.3953.212994
9377.631 4.448619397.4859.1453459420.61810.80026 9453.54 7.837259476.58611.10844
9519.3762.3820589532.5121.2114219552.2151.6248019568.6344.6392269667.0881.342173
9739.2810.73085110233.011.036952 10242.9-0.9436510275.861.26747110285.75 5.46292
10298.938.46019210318.717.32250510341.789.34801510364.8315.7292910454.0417.88482
#Mann= 3 , 0 , 0
8821.692    0.08       08821.692    0.08       010454.04    0.08       0
#XS Ineff= 2 , 0
       09589.412        10276.92       0
Bank Sta=8821.692,10454.04
Exp/Cntr=0.3,0.1

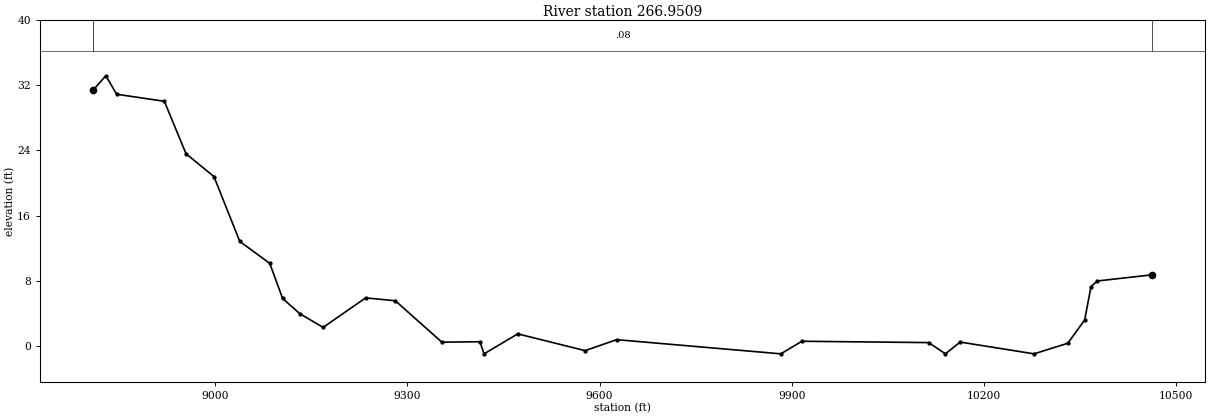
Type RM Length L Ch R = 1 ,266.9509,0.000000,0.000000,0.000000
XS GIS Cut Line= 6
1193930.50512118834719.7081504621193875.41670452834484.611005998
1193847.41572009 834323.68776197 1193818.5382577833986.341945187
1193824.82709133833701.3042447171193875.65843047833079.114782963
#Sta/Elev= 30
8809.64231.399548829.54433.16995 8846.49 30.89988920.84930.037288954.64923.59199
8998.27920.782139038.53712.820049085.32710.120029105.3525.8155199132.0523.945829
9168.6222.2503129234.9995.8783059281.3445.5222189353.8950.4350929413.2230.487136
9419.793  -0.9999472.3521.453853 9577.44-0.606589626.6530.7437119882.814  -0.999
9915.7120.54750310113.650.382842 10139.6  -0.99910162.650.44757910277.93  -0.999
10330.630.30110410356.97 3.1646410366.83 7.25936 10376.77.95523710462.718.715479
#Mann= 3 , 0 , 0
8809.642    0.08       08809.642    0.08       010462.71    0.08       0
#XS Ineff= 2 , 0
       09571.182                       0
Bank Sta=8809.642,10462.71
Exp/Cntr=0.3,0.1